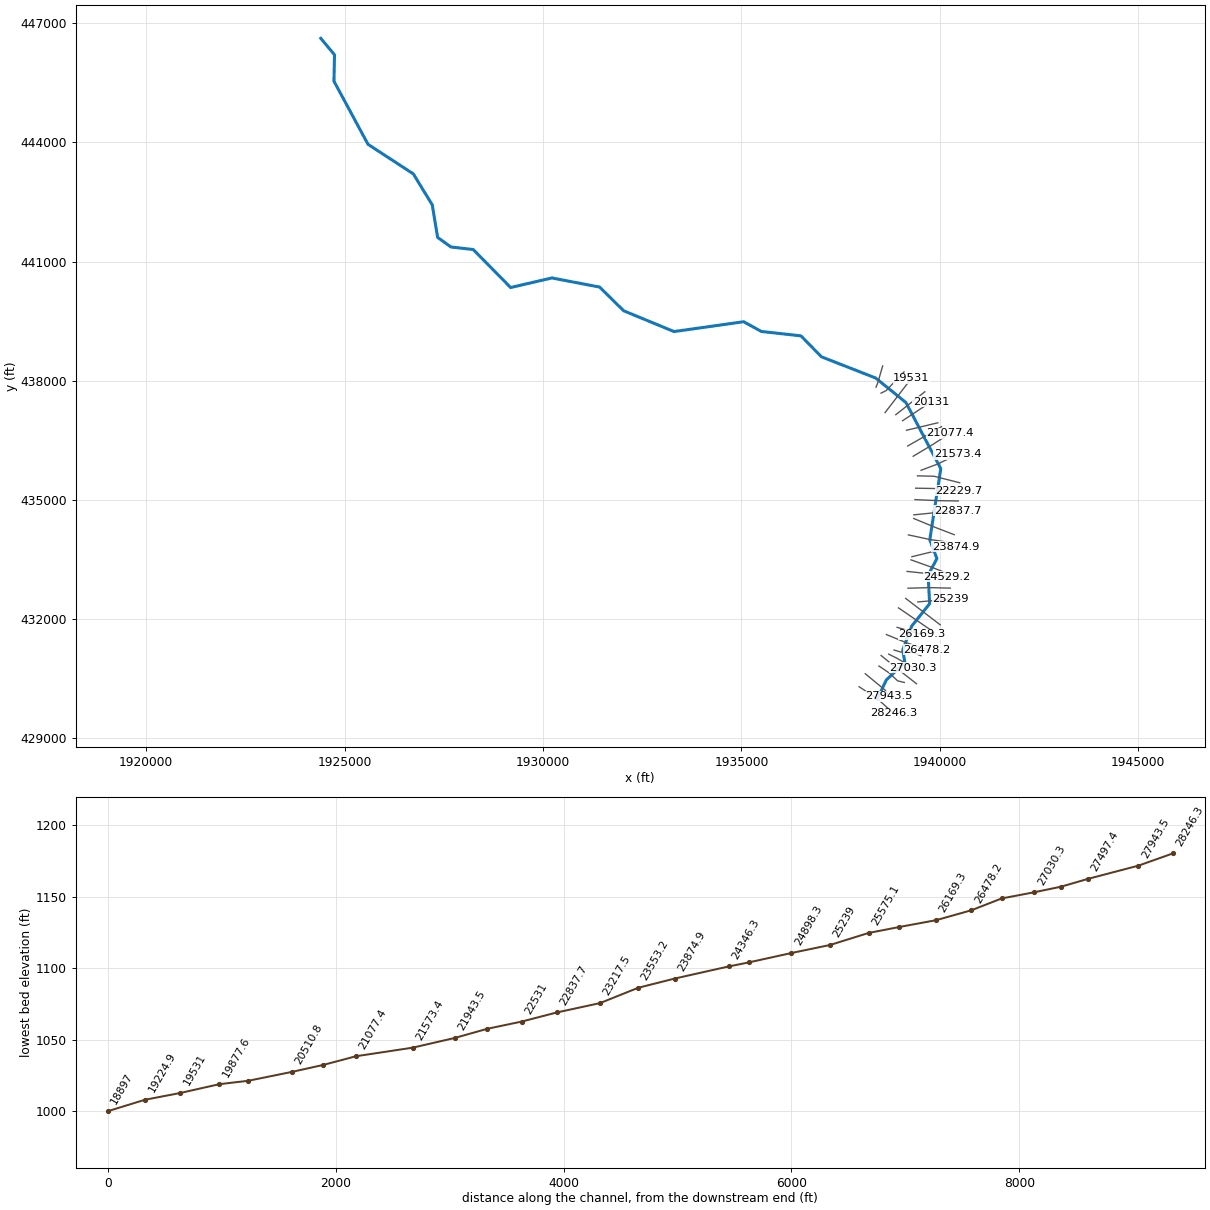
--- RichCreek.prj (project) ---

Proj Title=RichCreek
Current Plan=p01
Default Exp/Contr=0,0
English Units
Geom File=g01
Flow File=f01
Plan File=p01
BEGIN DESCRIPTION:
END DESCRIPTION:
DSS Export Rating Curves= 0
DSS Export Rating Curve Sorted= 0
DSS Export Volume Flow Curves= 0
DXF OffsetX= 0
DXF OffsetY= 0
DXF ScaleX= 0
DXF ScaleY= 0

--- RichCreek.p01 (plan) ---

Plan Title=Floodplain
Program Version=4.00
Geom File=g01
Flow File=f01
K Sum by GR=0
Std Step Tol=0.01
Critical Tol=0.01
Num of Std Step Trials=20
Max Error Tol=0.3
Flow Tol Ratio=0.001
Split Flow NTrial=30
Split Flow Tol=0.02
Split Flow Ratio=0.02
Log Output Level=0
Friction Slope Method=1
Unsteady Friction Slope Method=2
Unsteady Bridges Friction Slope Method=1
Global Log Level=0
CheckData=False
Run HTab=0
Run UNet=0
Run PostProcess=0
UNET Theta=0
UNET Theta Warmup=0
UNET ZTol=0
UNET ZSATol=0
UNET MxIter=0
UNET MaxInSteps=0
UNET DtIC=0
UNET DtMin=0
UNET MaxCRTS=0
UNET WFStab=0
UNET SFStab=0
UNET WFX=0
UNET SFX=0
UNET DSS MLevel=0
UNET DZMax Abort=0
UNET Convert EG Bridges=0
UNET Use Existing IB Tables=0
UNET Froude Limit=0
UNET Froude Power=0
Write IC File=0
Echo Input=False
Echo Output=False
Write Detailed=0

--- RichCreek.f01 (steady flow) ---

Flow Title=NFF Regression Equation
Program Version=4.00
Number of Profiles=1
Profile Names=P100yr
River Rch & RM=RichCreek,Main      ,28246.3
909.3817
River Rch & RM=RichCreek,Main      ,25846.3
961.7458
River Rch & RM=RichCreek,Main      ,22531
1040.240
River Rch & RM=RichCreek,Main      ,21943.5
1049.816
Boundary for River Rch & Prof#=RichCreek,Main      ,1
Up Type=0
Dn Type=3
Dn Slope=0.016452

--- RichCreek.g01 (geometry) ---

Geom Title=USGS 3m DEM
Program Version=4.10

River Reach=RichCreek       ,Main
Reach XY= 30
     1938422.735      429985.453     1938650.822       430468.88
     1939118.915      430903.856     1939064.228       431220.82
      1939290.79      431825.731     1939741.515      432387.215
     1939703.985      433103.509     1939924.471      433525.553
     1939745.581      433995.625     1940022.108      435788.056
     1939143.221      437454.203     1938381.068      438070.523
     1937016.485      438603.509     1936499.124      439131.286
      1935500.86      439242.398     1935056.415      439487.189
     1933301.078      439239.682      1932032.11      439763.231
     1931426.967      440359.255     1930224.818       440589.62
     1929184.888        440348.3     1928242.179      441304.898
     1927681.415      441369.134      1927344.61      441610.453
     1927210.929      442428.161     1926733.499      443209.412
     1925591.138      443954.203     1924733.499      445542.745
     1924747.388      446207.676      1924402.14      446622.641

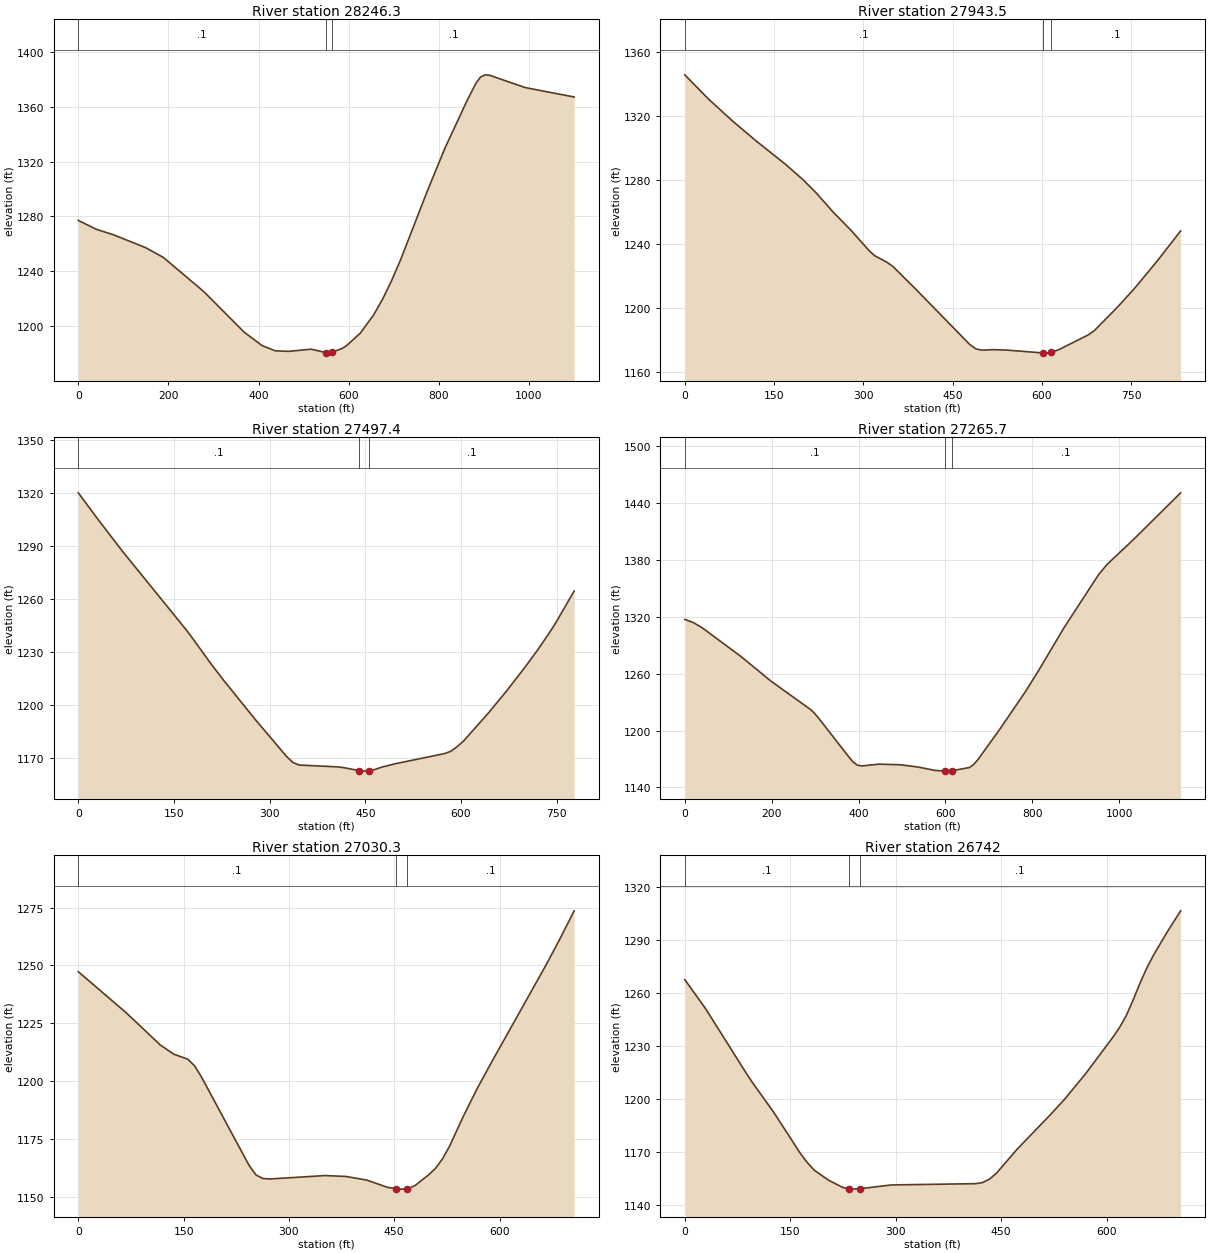
Type RM Length L Ch R = 1 ,28246.3 ,305.2,302.7,303.8
XS GIS Cut Line= 3
     1937963.938      430297.772     1938429.612      429992.713
     1938831.722      429626.164
#Sta/Elev= 30
       0 1277.11    39.8 1270.66    79.5 1266.46   149.1 1257.29   188.9 1250.11
   278.4  1225.3   367.8 1195.84   407.6    1186   437.4  1182.1   467.2 1181.74
   516.9  1183.3   549.2 1180.87   556.7 1180.44   564.2 1181.14   586.4 1183.95
   596.3 1186.12     626 1194.98   655.6 1208.27   675.4 1219.68   695.2 1233.04
     715 1248.04   774.3  1298.1   813.9 1329.72   863.4  1364.6   883.2 1377.26
     893 1381.55     903 1383.14   912.8 1382.85     992 1373.85  1100.8    1367
#Mann= 3 , 0 , 0
       0      .1       0   549.2    .045       0   564.2      .1       0
Bank Sta=549.2,564.2
XS Rating Curve= 0 ,0
Exp/Cntr=0.3,0.1

Type RM Length L Ch R = 1 ,27943.5 ,447.6,446.3,445.1
XS GIS Cut Line= 3
     1938119.255      430624.378     1938627.782      430205.617
     1938714.652      430054.595
#Sta/Elev= 30
       0  1345.8    39.9 1330.64    79.8 1317.08   119.8 1304.51   169.7 1289.72
   199.6 1279.92   219.6 1272.46   249.5 1259.93   279.5 1248.54   309.4 1235.99
   319.4 1232.67   339.4 1228.72   349.3 1226.16   389.3 1211.36   479.1 1177.14
   489.1 1174.52   499.1 1173.73     519 1174.04     539 1173.81     601 1172.02
   608.8 1171.87     616 1172.31   628.8 1174.14   668.4 1181.49   678.1 1183.33
   687.8 1185.85   726.5 1200.46   755.6 1212.34   794.3 1229.73     833 1248.24
#Mann= 3 , 0 , 0
       0      .1       0     601    .045       0     616      .1       0
Bank Sta=601,616
XS Rating Curve= 0 ,0
Exp/Cntr=0.3,0.1

Type RM Length L Ch R = 1 ,27497.4 ,229.9,231.3,233.1
XS GIS Cut Line= 4
     1938463.619      430819.502     1938733.363       430635.96
      1938935.17      430444.845     1939103.565      430404.751
#Sta/Elev= 30
       0 1320.07    29.7 1305.57    69.2 1286.98   168.1 1242.97     178 1238.25
   207.6 1223.45   227.4 1214.12   276.8 1192.01   326.3 1170.89   336.2 1167.46
   346.1 1165.96   405.7 1164.94   415.6 1164.53   439.9 1162.82   445.4 1162.52
   454.9 1162.67   465.2 1163.48   475.2 1164.73     495 1166.55   574.4 1172.49
   584.4 1173.82   594.3 1176.51   604.2 1179.67   642.7 1195.34   671.5 1207.97
   700.4 1221.43   719.6 1230.88   738.8 1241.01   748.5 1246.49   777.3 1264.48
#Mann= 3 , 0 , 0
       0      .1       0   439.9    .045       0   454.9      .1       0
Bank Sta=439.9,454.9
XS Rating Curve= 0 ,0
Exp/Cntr=0.3,0.1

Type RM Length L Ch R = 1 ,27265.7 ,231.9,235.3,238.4
XS GIS Cut Line= 3
     1938518.556      431083.347     1938989.194      430702.039
     1939410.871      430372.027
#Sta/Elev= 30
       0  1317.3    19.9 1313.93    39.7  1308.6   129.1 1278.22   198.6 1252.08
     288  1222.7   297.9 1218.54   307.8 1213.26   377.3  1172.3   387.3 1166.92
   397.2 1163.46   407.1 1162.62   446.8 1164.54   496.5 1163.86   536.2 1161.55
   575.9 1157.91   599.3 1157.22   605.7 1157.16   614.3 1157.51   655.3 1160.98
   665.2 1164.32   675.1 1169.55   724.7 1201.17   784.2 1241.18     814 1263.08
   873.4 1308.96   952.8 1364.84   972.6 1375.67  1032.1 1401.37  1141.2 1450.93
#Mann= 3 , 0 , 0
       0      .1       0   599.3    .045       0   614.3      .1       0
Bank Sta=599.3,614.3
XS Rating Curve= 0 ,0
Exp/Cntr=0.3,0.1

Type RM Length L Ch R = 1 ,27030.3 ,275.6,287.9,300.2
XS GIS Cut Line= 3
     1938710.643       431117.09     1938928.488      431008.836
     1939328.092      430774.953
#Sta/Elev= 30
       0 1247.29    68.1 1229.56   116.8  1215.6   136.2 1211.59   155.7 1209.49
   165.4 1206.66   175.2 1201.87   243.3 1163.49   253.1 1159.37     263 1157.85
   272.8 1157.64   351.6 1159.12   381.2 1158.73   410.7 1157.18   440.3 1154.03
   452.5 1153.43     460 1153.25   467.5 1153.37   469.8 1153.41   479.7 1154.82
   499.4 1159.53   509.2 1162.37   519.1 1166.51     529 1171.93   548.6 1184.87
   568.4 1196.89   588.1 1207.86   666.9 1250.55   686.6 1261.82   706.3 1273.63
#Mann= 3 , 0 , 0
       0      .1       0   452.5    .045       0   467.5      .1       0
Bank Sta=452.5,467.5
XS Rating Curve= 0 ,0
Exp/Cntr=0.3,0.1

Type RM Length L Ch R = 1 ,26742   ,273.1,263.6,254.7
XS GIS Cut Line= 4
      1938844.29      431221.334     1939020.704      431167.876
     1939279.913       431173.56     1939523.217      431076.996
#Sta/Elev= 30
       0 1267.52    29.1 1251.37    87.3 1214.63      97 1208.81   126.1 1192.65
   164.9 1168.81   174.6 1163.78   184.3 1159.56   204.3 1153.99   224.2 1149.94
     234 1148.88     249  1149.1     294 1151.25   413.7 1151.97   423.7  1152.6
   433.6 1154.55   443.6    1158   472.7 1171.44   521.2 1191.48   540.6 1199.91
   569.6 1213.92   608.4 1234.55   618.1 1240.15   627.8 1246.93   637.5 1255.69
   647.2 1265.12   656.9 1273.79   666.6 1281.24     686  1294.3   705.4 1306.49
#Mann= 3 , 0 , 0
       0      .1       0     234    .045       0     249      .1       0
Bank Sta=234,249
XS Rating Curve= 0 ,0
Exp/Cntr=0.3,0.1

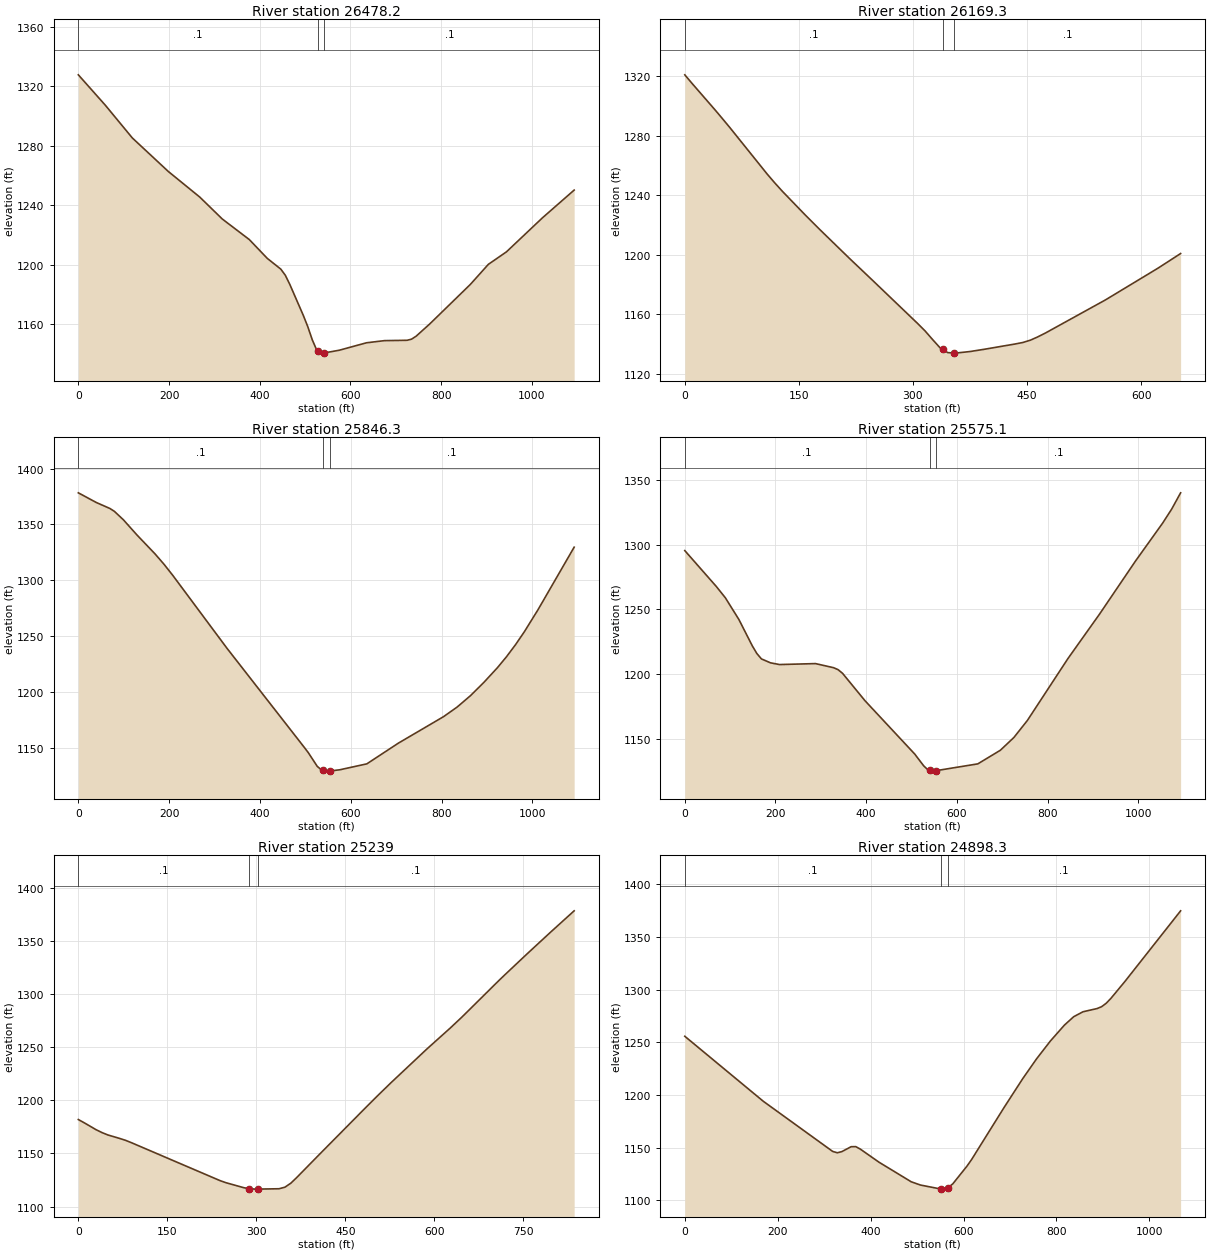
Type RM Length L Ch R = 1 ,26478.2 ,306.5,309,310.7
XS GIS Cut Line= 3
     1938652.777      431610.373     1939158.104      431404.297
     1939677.337      431230.029
#Sta/Elev= 30
       0 1327.77    59.5 1307.35   119.1 1285.32   198.4  1262.8   267.9 1245.55
   317.5 1230.82     377 1217.02   416.7 1204.36   446.5 1197.13   456.4 1193.04
   466.4 1186.85   496.1 1166.05     506 1158.44     516 1149.55   525.9 1142.55
   527.8 1142.19   535.8 1140.66   542.8 1140.82   575.6 1142.62   635.4 1147.61
   675.2 1149.06     725 1149.29   734.9 1150.06   744.9 1152.04   774.8 1160.24
   864.4 1186.83   904.2 1200.35   944.1 1208.75  1023.7 1231.69  1093.4 1250.28
#Mann= 3 , 0 , 0
       0      .1       0   527.8    .045       0   542.8      .1       0
Bank Sta=527.8,542.8
XS Rating Curve= 0 ,0
Exp/Cntr=0.3,0.1

Type RM Length L Ch R = 1 ,26169.3 ,330.3,322.9,315.6
XS GIS Cut Line= 2
     1938921.805      431792.007      1939548.61       431612.92
#Sta/Elev= 30
       0 1321.01     9.9 1315.02    39.5 1297.58    49.4 1291.58    59.3 1285.47
   108.6 1254.05   118.5 1248.16   128.4 1242.57     158 1226.88   177.8 1216.74
   217.3 1197.08   246.9  1182.7   306.2 1153.63   316.1 1148.55   325.9 1142.79
   335.8 1137.21     339  1136.2   345.7 1134.07     354 1133.78   355.6 1133.72
   375.3 1134.81   395.1 1136.42   434.6 1139.89   444.5 1140.88   454.4 1142.44
   464.2 1144.68   474.1 1147.23   553.1 1169.54   622.3 1190.94   651.9 1200.74
#Mann= 3 , 0 , 0
       0      .1       0     339    .045       0     354      .1       0
Bank Sta=339,354
XS Rating Curve= 0 ,0
Exp/Cntr=0.3,0.1

Type RM Length L Ch R = 1 ,25846.3 ,272.3,271.2,270
XS GIS Cut Line= 3
     1938957.439      432282.469     1939407.671      431973.589
     1939857.903      431664.708
#Sta/Elev= 30
       0 1378.35    39.7 1369.66    69.5 1364.33    79.4 1361.75    99.3 1354.16
     129 1340.64   168.8 1323.67   188.6 1314.39   208.5 1304.12   327.6 1238.93
   496.4 1150.88   506.3  1145.6   526.2 1133.22   536.1 1129.79   538.5 1129.58
     546 1128.94   553.5 1129.03   575.8 1130.15   635.4 1135.45   704.8    1154
   804.1 1177.69   833.9 1186.23   863.7 1196.58   893.4 1208.57   923.2 1221.71
   943.1 1231.51     963 1242.32   982.8 1254.16  1012.6 1273.73    1092 1329.64
#Mann= 3 , 0 , 0
       0      .1       0   538.5    .045       0   553.5      .1       0
Bank Sta=538.5,553.5
XS Rating Curve= 0 ,0
Exp/Cntr=0.3,0.1

Type RM Length L Ch R = 1 ,25575.1 ,319.3,335.9,352.5
XS GIS Cut Line= 2
     1939138.436      432520.309     1940007.134      431856.159
#Sta/Elev= 30
       0  1295.6    69.6 1267.76    89.5 1259.02   119.3 1242.22   149.1 1221.66
     159 1215.82     169 1211.69   188.9 1208.66   208.8 1207.31   288.3 1208.05
     328 1204.89     338 1203.37   347.9 1200.52   397.6 1179.22     507 1138.01
   526.9 1128.83   536.8 1125.52   539.9 1125.28   546.8 1124.74   554.9 1125.14
   646.2 1130.36   695.9  1140.9   725.7 1150.77   755.5 1163.98     845 1211.96
   914.6 1246.35   994.1 1287.57  1053.7 1316.82  1073.6 1327.65  1093.5 1340.36
#Mann= 3 , 0 , 0
       0      .1       0   539.9    .045       0   554.9      .1       0
Bank Sta=539.9,554.9
XS Rating Curve= 0 ,0
Exp/Cntr=0.3,0.1

Type RM Length L Ch R = 1 ,25239   ,341.9,340.6,338.2
XS GIS Cut Line= 2
     1939443.029      432432.177     1940275.757      432502.914
#Sta/Elev= 30
       0 1181.82      10 1178.75    29.8  1172.3    39.8 1169.58    49.8 1167.31
    69.6 1164.06    79.6 1162.26    89.5 1160.04   238.8 1124.38   248.7 1122.43
   278.6 1117.75   287.5 1116.77   298.5 1116.37   302.5 1116.39   338.3 1116.72
   348.2  1118.2   358.2 1121.97   368.1 1127.28   407.9 1149.91   487.5 1194.83
   507.4 1205.84   527.3 1216.61     587 1247.92   626.8 1267.84   646.7 1278.27
   706.4 1311.22   716.3 1316.57   756.1 1337.49   795.9    1358   835.7 1378.11
#Mann= 3 , 0 , 0
       0      .1       0   287.5    .045       0   302.5      .1       0
Bank Sta=287.5,302.5
XS Rating Curve= 0 ,0
Exp/Cntr=0.3,0.1

Type RM Length L Ch R = 1 ,24898.3 ,371.8,369,367.4
XS GIS Cut Line= 3
     1939196.694      432778.013     1939753.553      432792.282
     1940263.622      432779.659
#Sta/Elev= 30
       0  1255.8   169.1 1194.05   318.3  1146.5   328.3  1145.2   338.2 1146.34
   358.1 1150.97     368 1151.04     378 1148.63   417.8 1136.33   487.4 1117.67
   507.3 1114.58   550.8 1110.83     557  1110.7   565.8 1111.81     577 1115.78
   607.1 1132.36   617.1  1138.6   687.1 1188.08   727.1 1215.35   757.1 1234.31
   787.1 1251.38   817.2 1266.41   837.2 1274.39   857.2 1279.07   887.2 1282.08
   897.2 1283.87   907.2 1287.16   917.2 1291.76   947.2 1307.72  1067.3 1374.88
#Mann= 3 , 0 , 0
       0      .1       0   550.8    .045       0   565.8      .1       0
Bank Sta=550.8,565.8
XS Rating Curve= 0 ,0
Exp/Cntr=0.3,0.1

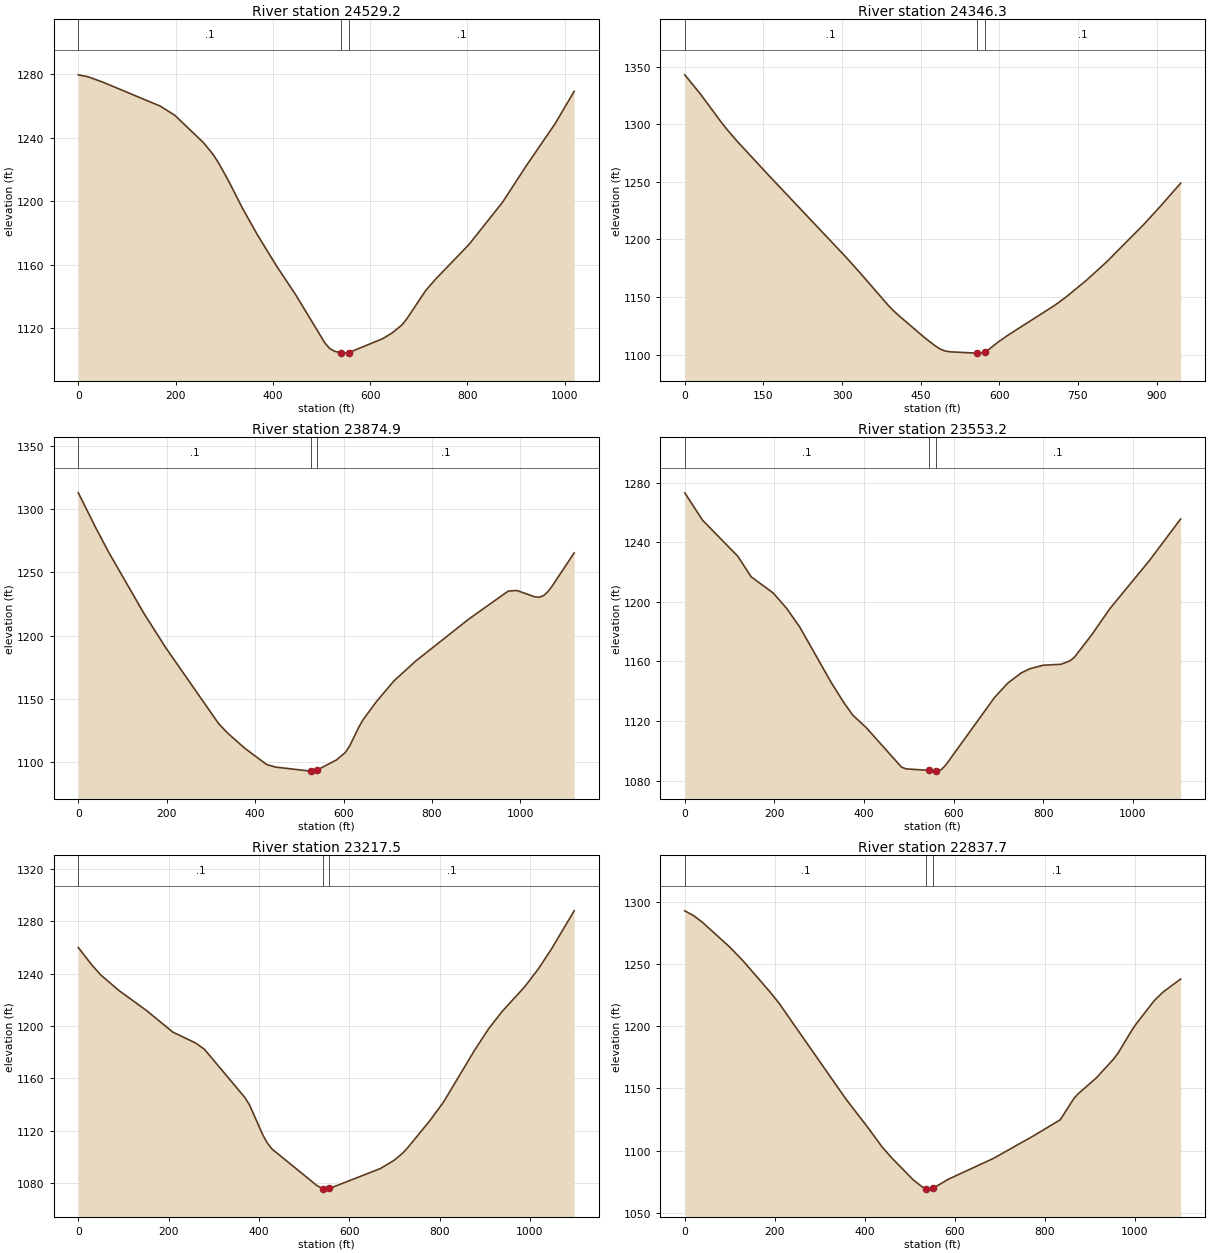
Type RM Length L Ch R = 1 ,24529.2 ,188.4,183,176.9
XS GIS Cut Line= 3
      1939173.69      433200.776     1939766.455      433137.834
      1940184.77      433072.347
#Sta/Elev= 30
       0 1279.47    19.9 1278.25    49.7 1274.95   168.9  1259.7   198.7 1253.92
   258.3 1236.44   278.2 1228.89   288.1  1224.1     308 1213.23   337.8  1195.3
   367.6 1179.06   407.3 1159.21   447.1  1140.9   506.7 1110.76   516.6 1107.19
   526.6 1105.39   540.8 1104.45   546.4 1104.22   555.8  1104.5   625.6 1113.28
   645.3 1116.94     665 1121.87   674.9  1125.6   714.3 1143.64     734 1150.64
   802.9 1172.51   871.8 1199.05     921 1222.18   980.1  1248.6  1019.5 1269.05
#Mann= 3 , 0 , 0
       0      .1       0   540.8    .045       0   555.8      .1       0
Bank Sta=540.8,555.8
XS Rating Curve= 0 ,0
Exp/Cntr=0.3,0.1

Type RM Length L Ch R = 1 ,24346.3 ,459.7,471,482.9
XS GIS Cut Line= 3
     1939272.325      433491.649     1939804.975      433300.687
     1940159.377      433163.227
#Sta/Elev= 30
       0 1343.07    29.8 1326.41    69.5 1301.96    79.4 1296.27    99.3 1285.66
   158.8  1256.4   307.7 1184.58   337.5 1169.43   387.2 1143.31   397.1  1138.6
     407 1134.42   456.6 1115.06   476.5    1108   486.4 1105.02   496.4 1103.16
   506.3 1102.41   555.9 1101.27   558.3 1101.28   565.8 1101.32   573.3  1102.5
   575.8  1102.9   595.9 1110.24   615.9 1116.65   705.9 1142.84   725.9 1149.47
   765.9  1164.4   805.9 1181.02     876 1213.24     906 1228.15     946 1248.91
#Mann= 3 , 0 , 0
       0      .1       0   558.3    .045       0   573.3      .1       0
Bank Sta=558.3,573.3
XS Rating Curve= 0 ,0
Exp/Cntr=0.3,0.1

Type RM Length L Ch R = 1 ,23874.9 ,329.6,321.8,314.7
XS GIS Cut Line= 3
     1939295.327      433570.688     1939892.083      433716.525
     1940389.403      433817.331
#Sta/Elev= 30
       0 1312.78    39.6 1285.04    69.4  1265.4   148.6 1217.38   198.2 1190.18
   317.1 1130.55   336.9  1123.2   376.5 1110.96   426.1 1098.07   445.9 1096.06
   525.1 1092.85   525.3 1092.85   540.3 1093.71   584.6 1101.81   604.4 1107.68
   614.3 1113.03   634.2 1127.35   644.2 1133.46     674 1147.59   713.8 1164.07
   763.6 1179.93     883 1212.89   972.5 1235.12   992.4  1235.6  1032.2 1230.64
  1042.2 1230.25  1052.1 1231.45    1062 1234.51    1072 1239.07  1121.8  1265.3
#Mann= 3 , 0 , 0
       0      .1       0   525.3    .045       0   540.3      .1       0
Bank Sta=525.3,540.3
XS Rating Curve= 0 ,0
Exp/Cntr=0.3,0.1

Type RM Length L Ch R = 1 ,23553.2 ,340.1,335.5,330.2
XS GIS Cut Line= 3
     1939207.269      434119.958     1939738.033       434005.94
     1940295.669      433923.318
#Sta/Elev= 30
       0 1273.23    39.5 1254.91   118.4 1230.62   148.1 1216.84   197.4 1205.96
     227 1195.75   256.6 1183.11   325.7 1146.41   355.3 1132.18   375.1 1123.91
   404.7 1115.64   483.6 1089.06   493.5 1087.87   544.9 1086.84   559.9 1086.41
   562.6 1086.35   572.5 1087.38   582.4 1090.41   691.2 1135.78   720.9 1145.46
   750.6 1152.27   770.3 1155.11     800 1157.46   839.6  1158.1   859.4  1160.4
   869.2  1162.7   908.8 1178.15   948.4 1195.34  1037.4 1227.94  1106.6 1255.67
#Mann= 3 , 0 , 0
       0      .1       0   544.9    .045       0   559.9      .1       0
Bank Sta=544.9,559.9
XS Rating Curve= 0 ,0
Exp/Cntr=0.3,0.1

Type RM Length L Ch R = 1 ,23217.5 ,368.6,379.7,390.1
XS GIS Cut Line= 3
     1939341.029      434532.996     1939857.335      434319.274
     1940360.713      434125.478
#Sta/Elev= 30
       0 1259.84    29.9 1246.58    49.9 1238.87    89.8 1227.12   149.7 1212.15
   209.6 1195.29   259.4 1187.12   279.4 1182.24   369.2 1145.34   379.2 1139.81
   409.1 1116.65   419.1 1110.52   429.1 1106.17   528.9 1078.21   541.1 1076.09
   548.8 1075.62   556.1  1076.1   668.7 1091.27   698.6 1097.39   718.6 1103.11
   728.6 1106.84   778.6 1127.82   808.5 1141.81   878.4 1181.96   908.4 1197.72
   938.4    1211   988.3 1229.76  1018.3 1243.24  1048.2 1258.87  1098.2 1287.83
#Mann= 3 , 0 , 0
       0      .1       0   541.1    .045       0   556.1      .1       0
Bank Sta=541.1,556.1
XS Rating Curve= 0 ,0
Exp/Cntr=0.3,0.1

Type RM Length L Ch R = 1 ,22837.7 ,310,306.7,304.6
XS GIS Cut Line= 3
     1939343.782      434624.688     1939888.074      434680.121
     1940440.613      434725.038
#Sta/Elev= 30
       0 1292.61    19.9 1288.68    39.8  1283.2    99.5 1263.61   129.3 1252.49
     189 1227.58   208.9 1218.64   358.1 1141.35   407.8 1118.02   437.7 1103.24
   457.6 1094.98   507.3 1076.56   527.2 1070.92   536.9 1069.27   547.1 1069.06
   551.9 1069.86   586.7 1077.22   685.7 1093.75   774.8 1111.88   834.2 1124.82
   863.9 1141.62   873.8 1145.64   913.4 1158.12     953  1173.7   962.9 1178.54
   992.6 1196.36  1002.5 1201.62  1042.1 1220.16  1061.9  1227.2  1101.5 1237.85
#Mann= 3 , 0 , 0
       0      .1       0   536.9    .045       0   551.9      .1       0
Bank Sta=536.9,551.9
XS Rating Curve= 0 ,0
Exp/Cntr=0.3,0.1

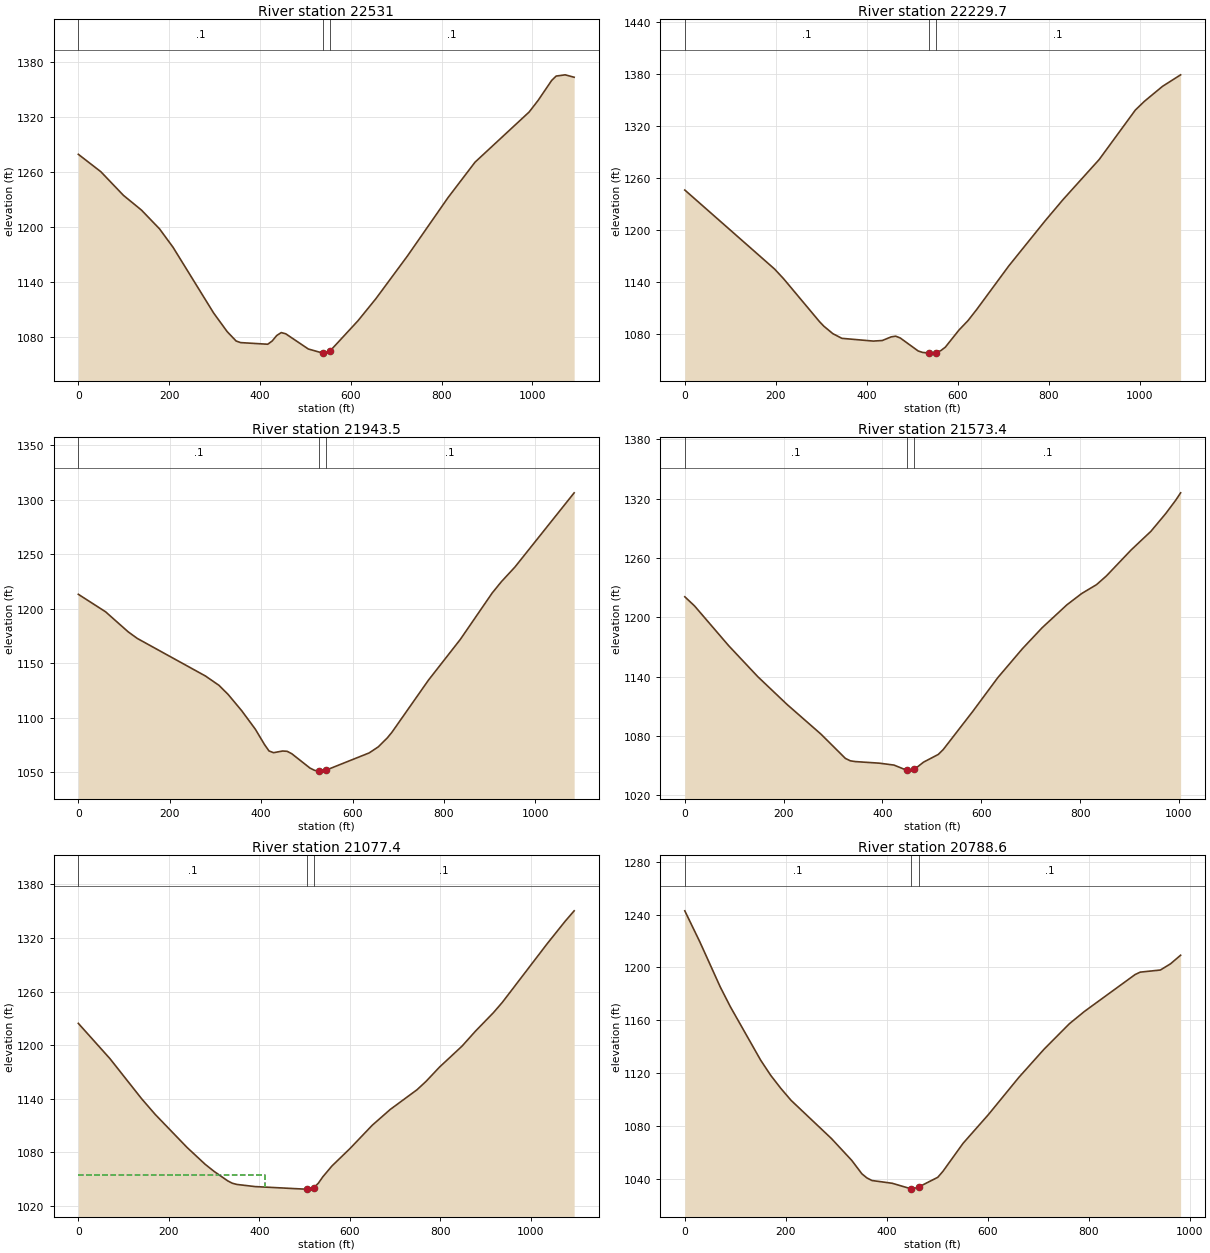
Type RM Length L Ch R = 1 ,22531   ,302.3,301.2,299.5
XS GIS Cut Line= 3
     1939372.092      435008.523     1939917.803      434983.241
     1940463.678      434974.293
#Sta/Elev= 30
       0 1279.64    49.7  1260.6    99.3 1234.88   139.1 1218.76   178.8 1198.34
   208.6 1178.21     298 1106.52   327.8  1086.2   347.6 1075.91   357.6 1074.18
   417.2  1072.4   427.1 1075.97     437 1081.92     447 1085.12   456.9 1083.78
   506.6 1067.21   538.8 1062.71   546.3  1062.7   553.8 1064.69   615.8  1097.9
   655.5 1122.13     725 1168.73   814.3 1232.34   873.9 1271.07     993 1325.77
  1012.8 1338.46  1042.6 1360.19  1052.5 1364.99  1072.4 1366.36  1092.2 1363.72
#Mann= 3 , 0 , 0
       0      .1       0   538.8    .045       0   553.8      .1       0
Bank Sta=538.8,553.8
XS Rating Curve= 0 ,0
Exp/Cntr=0.3,0.1

Type RM Length L Ch R = 1 ,22229.7 ,289.7,286.2,282.8
XS GIS Cut Line= 3
      1939389.57      435296.234     1939902.775      435286.879
     1940477.341      435232.342
#Sta/Elev= 30
       0 1246.07   197.4 1154.81   217.2 1143.66   296.1 1094.12     306 1088.68
   325.7 1080.12   345.5 1074.75   414.6 1071.58   434.3 1072.24   454.1 1076.48
   463.9 1077.24   473.8 1075.18   513.3 1060.13   523.2 1058.45   536.9 1057.86
   543.1 1057.67   551.9 1058.08     563 1060.57     573 1064.58   602.8 1084.23
   622.8 1095.21   642.6 1108.53   712.3 1158.27   791.9 1210.16   831.7 1234.96
   911.3 1281.31   990.9 1338.48  1010.8 1348.56  1050.6 1365.84  1090.4 1379.13
#Mann= 3 , 0 , 0
       0      .1       0   536.9    .045       0   551.9      .1       0
Bank Sta=536.9,551.9
XS Rating Curve= 0 ,0
Exp/Cntr=0.3,0.1

Type RM Length L Ch R = 1 ,21943.5 ,356,370.1,385.9
XS GIS Cut Line= 3
      1939435.01      435606.295     1939851.989       435596.94
     1940499.231      435433.232
#Sta/Elev= 30
       0 1213.38    59.6 1197.34   109.2 1178.91   129.1 1172.88   278.1 1138.46
   307.8 1129.87   327.7 1121.56   357.5 1106.58   387.3 1089.63   407.2 1075.68
   417.1 1069.74     427 1068.14     447 1069.67   456.9 1069.39   466.9  1067.2
   506.8 1054.03   516.7 1051.96   526.4 1051.25   526.7 1051.23   541.4 1052.04
   636.3 1067.93   656.2 1073.48   676.2 1081.83   686.1 1086.89   765.8 1134.57
   835.6 1171.98   905.4 1214.58   925.3 1224.85   955.2 1238.41  1084.7 1306.43
#Mann= 3 , 0 , 0
       0      .1       0   526.4    .045       0   541.4      .1       0
Bank Sta=526.4,541.4
XS Rating Curve= 0 ,0
Exp/Cntr=0.3,0.1

Type RM Length L Ch R = 1 ,21573.4 ,492.2,496,498
XS GIS Cut Line= 3
      1939525.89      435746.625     1939949.551      435907.001
     1940444.665      436147.576
#Sta/Elev= 30
       0 1220.72    19.7 1211.49    88.6 1171.38   147.7 1139.96   206.8 1111.91
   275.7 1081.78     325  1057.3   334.8 1054.89   344.7 1054.09   393.9 1052.46
   423.5 1050.52   449.3 1045.27     453 1044.42   464.3 1046.08     483 1053.45
     513 1061.29   523.1 1066.26   583.1 1105.01   633.2 1138.79   683.2 1168.16
   723.2 1189.41   773.3 1212.58   803.3 1224.04   833.3    1233   853.3 1241.82
   903.4 1268.11   943.4 1286.94   973.4 1304.91   993.5 1318.32  1003.5 1325.85
#Mann= 3 , 0 , 0
       0      .1       0   449.3    .045       0   464.3      .1       0
Bank Sta=449.3,464.3
XS Rating Curve= 0 ,0
Exp/Cntr=0.3,0.1

Type RM Length L Ch R = 1 ,21077.4 ,289.1,288.5,287.8
XS GIS Cut Line= 3
     1939326.868      436099.596     1939799.232      436382.046
     1940257.622      436677.209
#Sta/Elev= 30
       0  1224.3      70 1184.65   140.1 1139.63   170.1 1122.08   240.2  1085.2
   280.2 1066.31   300.2 1058.24   330.2 1047.68   340.2 1045.05   350.2  1043.7
   390.3  1041.3   500.3 1038.44   505.4 1038.45   520.4 1040.05   530.4 1045.13
   540.4 1052.34   560.3 1064.35   599.9 1083.76   649.5 1110.09   689.2 1127.77
   748.6 1149.96   768.4  1159.3   798.2 1175.31   847.8 1198.75   877.5 1215.54
   917.1 1236.23     937  1247.9  1036.1 1313.66  1075.7 1338.78  1095.6 1350.47
#Mann= 3 , 0 , 0
       0      .1       0   505.4    .045       0   520.4      .1       0
#XS Ineff= 2 , 0
          411.59 1054.74
Permanent Ineff=
       F       F
Bank Sta=505.4,520.4
XS Rating Curve= 0 ,0
Exp/Cntr=0.3,0.1

Type RM Length L Ch R = 1 ,20788.6 ,284.3,278,271.8
XS GIS Cut Line= 2
     1939189.099      436358.728     1940041.768      436845.204
#Sta/Elev= 30
       0 1242.79      30 1219.14    70.1  1185.3    90.2 1170.26   150.3  1129.8
   170.3 1118.29   190.3 1108.44   210.4 1099.47   290.5 1070.53   330.6 1054.04
   350.6 1043.93   360.6 1040.79   370.6 1038.84   410.7 1036.76   448.5  1032.5
   450.8 1032.33   463.5 1034.03   500.9 1041.28   510.9 1045.69   550.9 1066.94
     601 1088.64   661.1  1116.7   711.2  1138.1   761.3 1157.35   791.4 1166.75
   891.5 1194.58   901.6 1196.42   941.6 1198.02   961.6  1202.7   981.7 1209.22
#Mann= 3 , 0 , 0
       0      .1       0   448.5    .045       0   463.5      .1       0
Bank Sta=448.5,463.5
XS Rating Curve= 0 ,0
Exp/Cntr=0.3,0.1

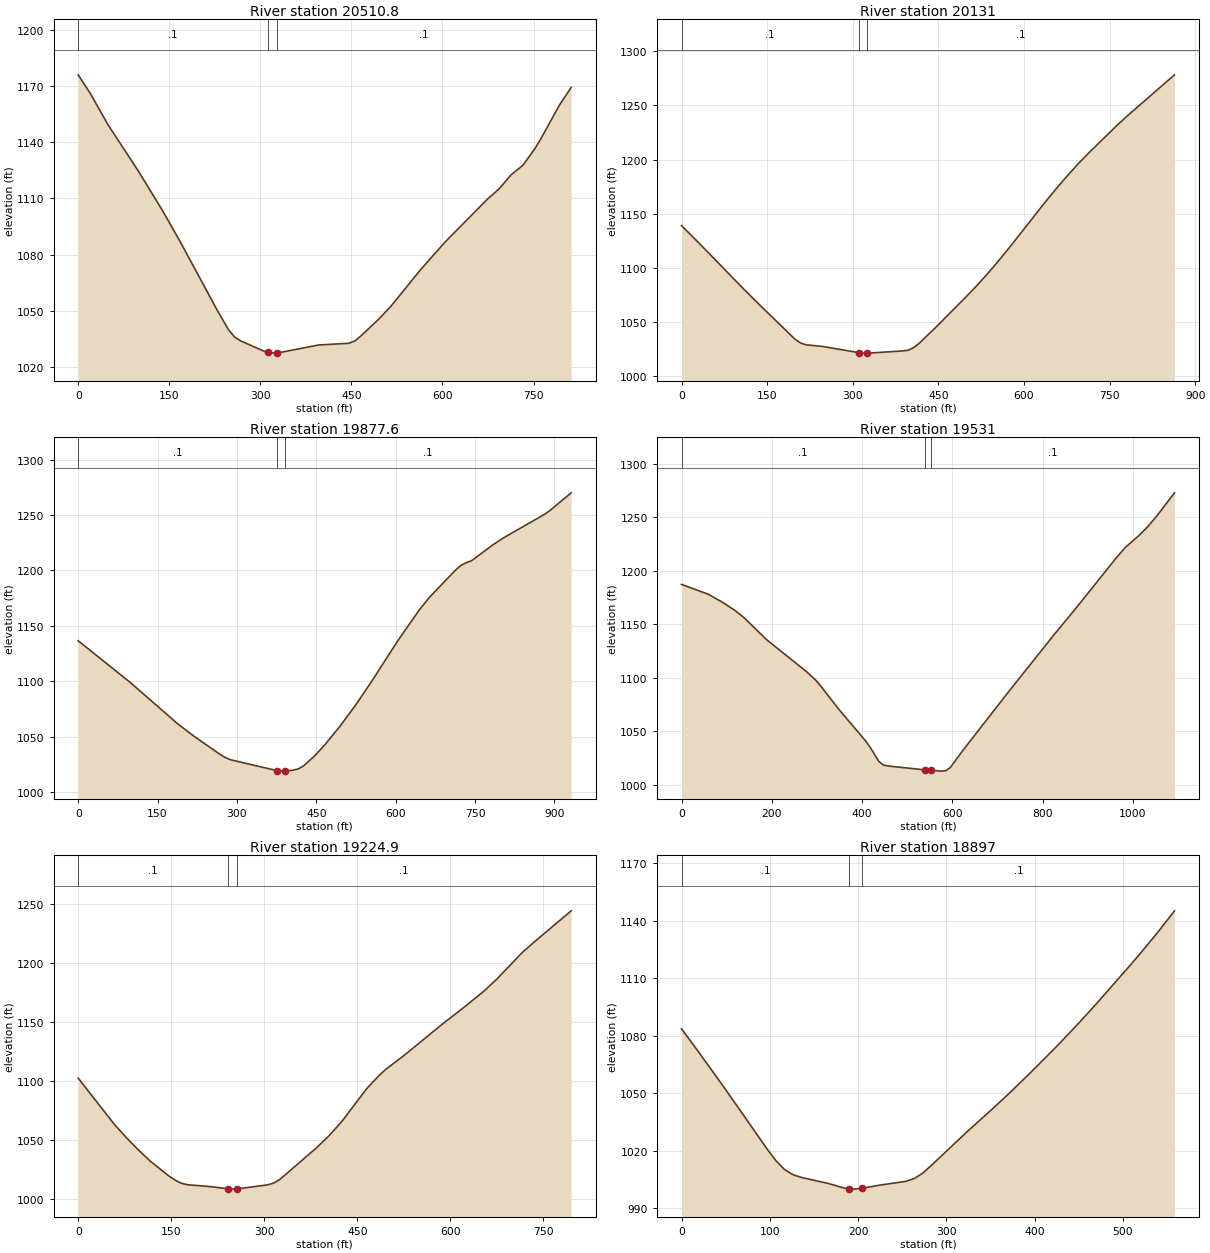
Type RM Length L Ch R = 1 ,20510.8 ,371.8,379.7,387.7
XS GIS Cut Line= 2
     1939158.361      436754.324     1939948.215      436942.766
#Sta/Elev= 30
       0 1175.94    19.8 1166.08    49.5  1149.1      99 1124.64   138.6 1103.65
   168.4 1086.67   227.8 1051.02   247.6  1039.9   257.5 1036.04   267.4 1033.99
     307  1028.3   312.9 1027.84   326.8 1027.41   327.9 1027.45   396.1 1031.76
   445.6 1032.67   455.5 1033.86   465.4  1036.5   495.1 1045.58   514.9 1052.36
   564.4 1072.11   604.1 1086.61   673.4 1109.38   693.2 1115.04     713 1122.54
   732.8 1127.74   752.6 1136.72   762.5 1142.04   792.2 1159.51     812 1169.21
#Mann= 3 , 0 , 0
       0      .1       0   312.9    .045       0   327.9      .1       0
Bank Sta=312.9,327.9
XS Rating Curve= 0 ,0
Exp/Cntr=0.3,0.1

Type RM Length L Ch R = 1 ,20131   ,251.5,253.4,255.3
XS GIS Cut Line= 3
      1939060.56      436994.565     1939325.551      437169.925
     1939780.878      437471.244
#Sta/Elev= 30
       0 1139.03    29.8  1123.3   109.2 1080.28     139 1064.68   198.6 1034.21
   208.5 1030.58   218.5 1028.93   248.2 1027.32   310.3 1021.72   317.8 1021.31
   325.3 1021.26   327.7 1021.24   387.2 1023.26   397.2 1023.94   407.1  1026.4
     417 1030.58   446.8 1045.74   496.4 1072.07   516.3 1082.98   536.2 1094.54
     556 1106.78   575.9 1119.62   635.4 1159.48   655.3 1172.25   675.1 1184.45
     695 1196.08   714.8 1206.74   764.5 1232.33   784.3 1241.78   863.8 1278.21
#Mann= 3 , 0 , 0
       0      .1       0   310.3    .045       0   325.3      .1       0
Bank Sta=310.3,325.3
XS Rating Curve= 0 ,0
Exp/Cntr=0.3,0.1

Type RM Length L Ch R = 1 ,19877.6 ,341,346.6,352.2
XS GIS Cut Line= 2
     1938888.394      437145.909     1939619.945      437722.976
#Sta/Elev= 30
       0 1136.54    99.1 1098.63   188.3 1061.46   218.1 1050.65   267.6  1034.2
   277.6 1031.31   287.5 1029.19   376.3 1019.26   386.6 1018.87   391.3 1019.01
   406.4 1019.72   416.3 1020.95   426.2 1023.68     446 1032.16   465.9 1042.48
   495.6 1059.86   525.4 1079.16   555.1 1100.16   604.6 1136.86   644.3 1164.06
   664.1 1175.84   713.7 1200.54   723.6 1204.59   733.5 1207.03   743.4  1208.7
   783.1 1222.84   802.9 1229.13   882.2 1250.83   892.1 1254.19   931.8 1270.03
#Mann= 3 , 0 , 0
       0      .1       0   376.3    .045       0   391.3      .1       0
Bank Sta=376.3,391.3
XS Rating Curve= 0 ,0
Exp/Cntr=0.3,0.1

Type RM Length L Ch R = 1 ,19531   ,308.5,306.1,303.6
XS GIS Cut Line= 2
     1938618.264      437198.412     1939284.069      438063.957
#Sta/Elev= 30
       0 1187.29    59.6 1178.06    89.4  1170.9   119.1 1162.76     139 1155.95
   188.6 1135.55     278  1105.3   297.8 1097.49   307.8 1092.52   347.4 1071.03
     407 1041.25     417 1035.53   436.8 1021.94   446.7 1018.45   456.6  1017.5
   538.5 1013.81   553.5 1013.39   575.8 1012.64   585.7 1013.12   595.6 1016.12
   625.4 1033.22   724.7 1086.99     824  1139.6   873.6 1164.96     963 1212.12
   982.8 1221.76  1012.6 1232.78  1032.4 1241.15  1052.3 1251.04    1092 1272.95
#Mann= 3 , 0 , 0
       0      .1       0   538.5    .045       0   553.5      .1       0
Bank Sta=538.5,553.5
XS Rating Curve= 0 ,0
Exp/Cntr=0.3,0.1

Type RM Length L Ch R = 1 ,19224.9 ,316.9,327.8,338.8
XS GIS Cut Line= 3
     1938518.191      437688.517     1938647.829       437755.34
     1939096.523      438223.877
#Sta/Elev= 30
       0  1102.1    58.3  1062.9    77.8 1051.55    97.2 1041.09   116.7 1031.44
   145.8 1019.25   155.8 1015.72   165.8 1013.05   175.8 1011.73   215.7 1009.95
   241.4 1008.23   245.6 1007.96   256.4 1008.16   305.5 1011.59   315.5 1013.19
   325.5 1016.36   385.4  1043.6   405.3 1053.77   425.3 1065.56   465.2  1093.3
   485.2 1104.43   495.2  1109.3   525.1 1121.27     585 1147.06   624.9 1163.44
   654.8 1176.26   674.8 1186.04   714.7 1208.05   734.7  1217.4   794.6 1243.97
#Mann= 3 , 0 , 0
       0      .1       0   241.4    .045       0   256.4      .1       0
Bank Sta=241.4,256.4
XS Rating Curve= 0 ,0
Exp/Cntr=0.3,0.1

Type RM Length L Ch R = 1 ,18897   ,186.1,188.3,190.3
XS GIS Cut Line= 3
      1938392.34      437840.874     1938435.107      437949.574
     1938558.062      438373.681
#Sta/Elev= 30
       0 1083.64    19.5 1071.46    48.7 1052.72    97.3 1020.67   107.1 1014.68
   116.8 1010.09   126.6 1007.39   136.4 1005.96   165.9 1002.93   185.5 1000.32
   189.7 1000.15   195.3  999.92   204.7 1000.39   224.8 1002.03   254.2 1003.98
     264 1005.51   273.8 1008.48   283.6 1012.56   322.9 1029.67   352.3 1041.88
   371.9 1050.28   391.6 1059.08     421 1072.62   430.8 1077.29   450.4 1086.85
   470.1 1096.82   509.3 1117.42   519.1 1122.72   538.8 1133.67   558.4 1145.26
#Mann= 3 , 0 , 0
       0      .1       0   189.7    .045       0   204.7      .1       0
Bank Sta=189.7,204.7
XS Rating Curve= 0 ,0
Exp/Cntr=0.3,0.1