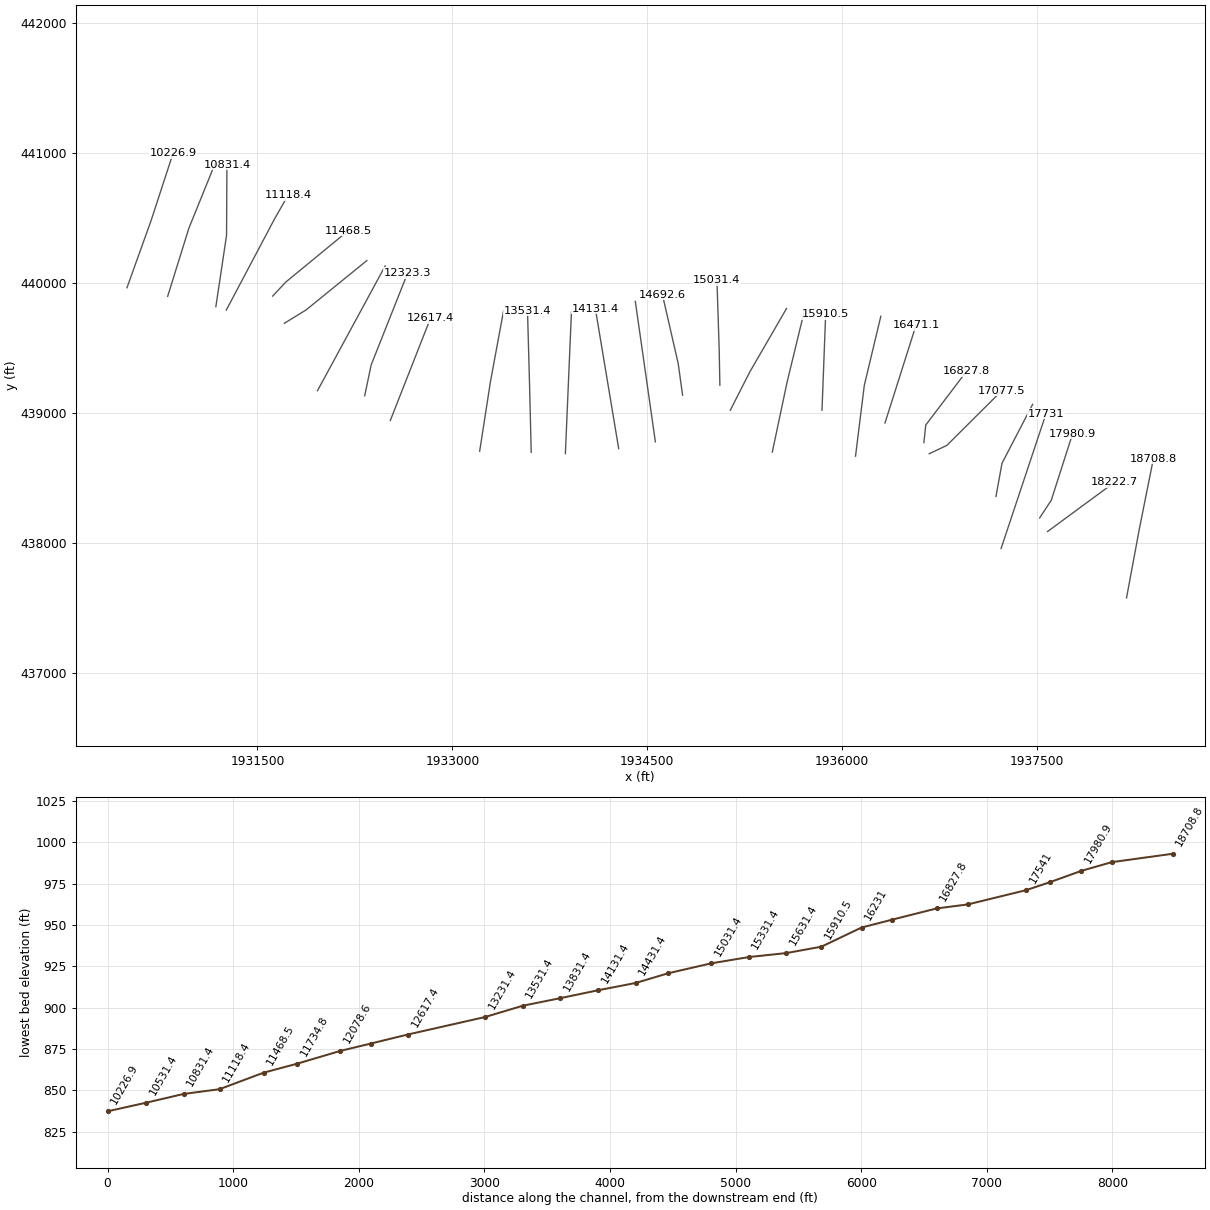
HEC-RAS study RichCreek.prj: RichCreek

--- RichCreek.g01 (geometry) --- (continued)

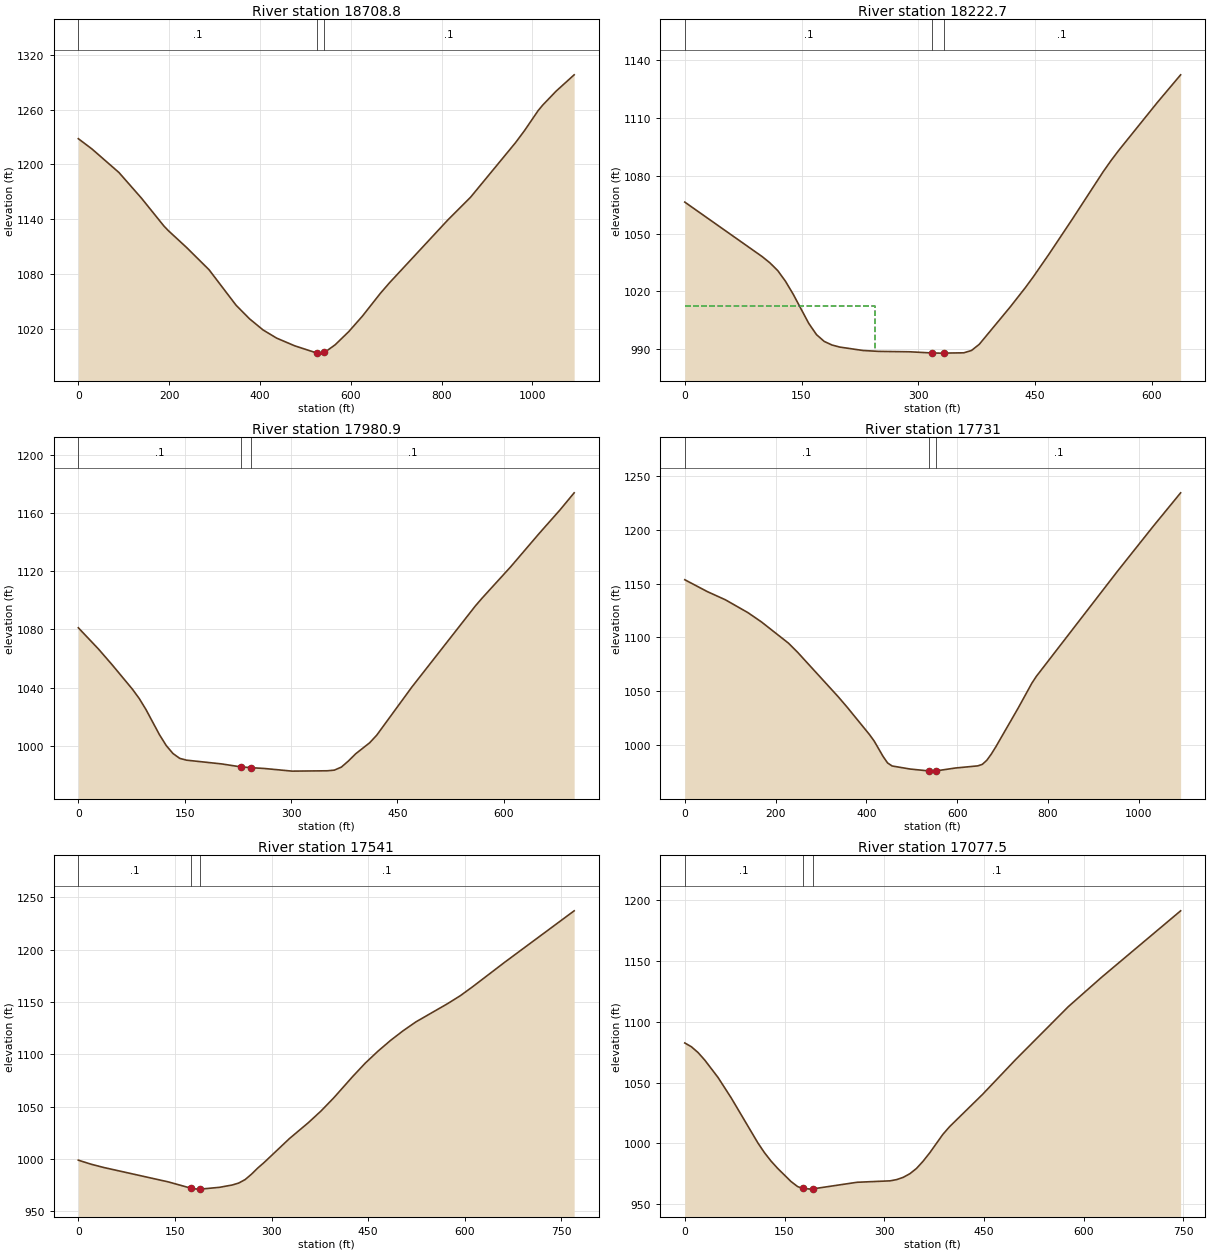
Type RM Length L Ch R = 1 ,18708.8 ,503,485.4,468
XS GIS Cut Line= 3
     1938187.448      437574.201     1938287.315       438110.98
     1938394.301      438646.455
#Sta/Elev= 30
       0 1228.26    29.8 1217.08    89.3 1191.26     139 1163.07   188.6 1132.42
   198.5 1127.29   238.2 1109.03   287.9 1084.52   347.4  1045.6   377.2 1030.63
     407 1018.43   436.8 1009.51   476.5 1001.09   525.9  993.06   536.1  993.15
   540.9  994.13     546  995.17   565.8 1002.28   595.6 1016.67   625.4  1033.5
   665.1 1058.59     685 1070.04     814 1139.24   863.7 1163.98     963    1224
   982.8 1237.24  1012.6 1259.03  1022.6 1265.04  1052.3 1280.45    1092 1298.33
#Mann= 3 , 0 , 0
       0      .1       0   525.9    .045       0   540.9      .1       0
Bank Sta=525.9,540.9
XS Rating Curve= 0 ,0
Exp/Cntr=0.3,0.1

Type RM Length L Ch R = 1 ,18222.7 ,227.7,242.5,257.3
XS GIS Cut Line= 2
     1937579.766      438085.003     1938092.971      438462.779
#Sta/Elev= 30
       0 1066.41    99.6 1038.07   109.5 1034.82   119.5 1030.82   129.4  1025.3
   139.4 1018.52   159.3 1003.43   169.3  997.57   179.2  994.06   189.2  992.19
   199.1  991.13     229  989.35   248.9  988.89   288.8  988.68   317.8  988.06
   328.6  987.98   332.8     988   358.5  988.14   368.4  989.34   378.4  992.54
   418.2 1011.96   438.1 1022.23   448.1 1027.75     468 1039.37   497.9 1057.49
   537.7 1082.21   547.6 1087.89   557.6 1093.24   607.4 1118.23   637.2 1132.52
#Mann= 3 , 0 , 0
       0      .1       0   317.8    .045       0   332.8      .1       0
#XS Ineff= 2 , 0
          244.09 1012.34
Permanent Ineff=
       F       F
Bank Sta=317.8,332.8
XS Rating Curve= 0 ,0
Exp/Cntr=0.3,0.1

Type RM Length L Ch R = 1 ,17980.9 ,250.1,249.8,249.5
XS GIS Cut Line= 3
     1937519.179      438190.139     1937608.277      438325.568
     1937772.218      438836.991
#Sta/Elev= 30
       0 1081.09    28.6  1066.4    47.7 1055.68    76.3 1038.92    85.8 1032.61
    95.4 1024.96   114.4 1007.72     124 1000.24   133.5  994.78     143  991.47
   152.6  990.23   201.9  987.67   228.8  985.65   243.8  985.06   261.6  984.56
   301.4  982.71   351.1  982.94     361  983.39     371  985.49   380.9  989.68
   390.9  994.52   410.8 1002.15   420.7 1007.32   470.4 1040.44   559.9 1096.08
   569.9  1101.7   609.7 1122.94   649.4 1145.55   679.3    1162   699.2  1173.7
#Mann= 3 , 0 , 0
       0      .1       0   228.8    .045       0   243.8      .1       0
Bank Sta=228.8,243.8
XS Rating Curve= 0 ,0
Exp/Cntr=0.3,0.1

Type RM Length L Ch R = 1 ,17731   ,186.5,189.8,193
XS GIS Cut Line= 3
     1937222.295      437954.741     1937394.956      438472.722
     1937567.616      438990.703
#Sta/Elev= 30
       0 1153.62    49.6 1142.61    89.4    1135     139 1123.08   168.8 1114.45
   228.3 1094.73   248.2 1086.37   337.5 1045.15   357.4 1035.36     407  1009.7
     417 1003.86   436.8  989.46   446.7  983.44   456.6  980.66   496.4  977.81
   538.5  976.02     546  975.88   553.5  976.11   595.6  978.75   645.3  980.76
   655.2  982.16   665.1  985.92     675  991.68     685  998.46   734.6 1034.72
   764.4 1057.58   774.3 1063.92     953 1161.55  1032.4 1203.64    1092 1234.34
#Mann= 3 , 0 , 0
       0      .1       0   538.5    .045       0   553.5      .1       0
Bank Sta=538.5,553.5
XS Rating Curve= 0 ,0
Exp/Cntr=0.3,0.1

Type RM Length L Ch R = 1 ,17541   ,477.5,463.7,450
XS GIS Cut Line= 3
     1937182.908       438355.75     1937229.239       438610.57
     1937464.943      439063.941
#Sta/Elev= 30
       0  998.74    19.9  994.86    39.8  991.69   139.5  978.01   174.4  972.04
   179.3  971.37   189.3  971.06   189.4  971.06   219.2  972.78   239.1  975.02
     249  976.86     259  980.17   268.8  985.27   278.6   991.2   288.5  996.49
   327.8 1019.36   357.3 1034.61   376.9 1045.76   396.6 1058.26     426 1078.65
   445.7 1091.56   465.4 1102.95     485 1113.26   504.7 1122.58   524.3 1130.94
   573.4 1148.33   593.1  1155.9   612.8 1164.72   661.9 1187.82     770 1237.08
#Mann= 3 , 0 , 0
       0      .1       0   174.4    .045       0   189.4      .1       0
Bank Sta=174.4,189.4
XS Rating Curve= 0 ,0
Exp/Cntr=0.3,0.1

Type RM Length L Ch R = 1 ,17077.5 ,246.3,249.7,253.2
XS GIS Cut Line= 3
     1936669.184      438683.742     1936804.613      438747.892
     1937226.938      439168.435
#Sta/Elev= 30
       0 1082.56      10 1079.41      20 1074.66      30 1068.52      50 1054.21
    69.9 1037.34   109.9 1000.46   119.9  992.35   129.9  985.38   139.9  979.37
   159.8  968.68   169.7  964.54   177.1  963.07   189.6  962.44   192.1  962.61
   259.1  968.07   308.8  969.25   318.7  970.27   328.6  972.14   338.6  975.12
   348.5  979.43   358.4  985.37   368.4  992.26   388.2 1007.46   398.2 1013.73
   447.8 1040.26   497.5 1068.84     577 1112.47   626.6  1136.4   745.8 1191.16
#Mann= 3 , 0 , 0
       0      .1       0   177.1    .045       0   192.1      .1       0
Bank Sta=177.1,192.1
XS Rating Curve= 0 ,0
Exp/Cntr=0.3,0.1

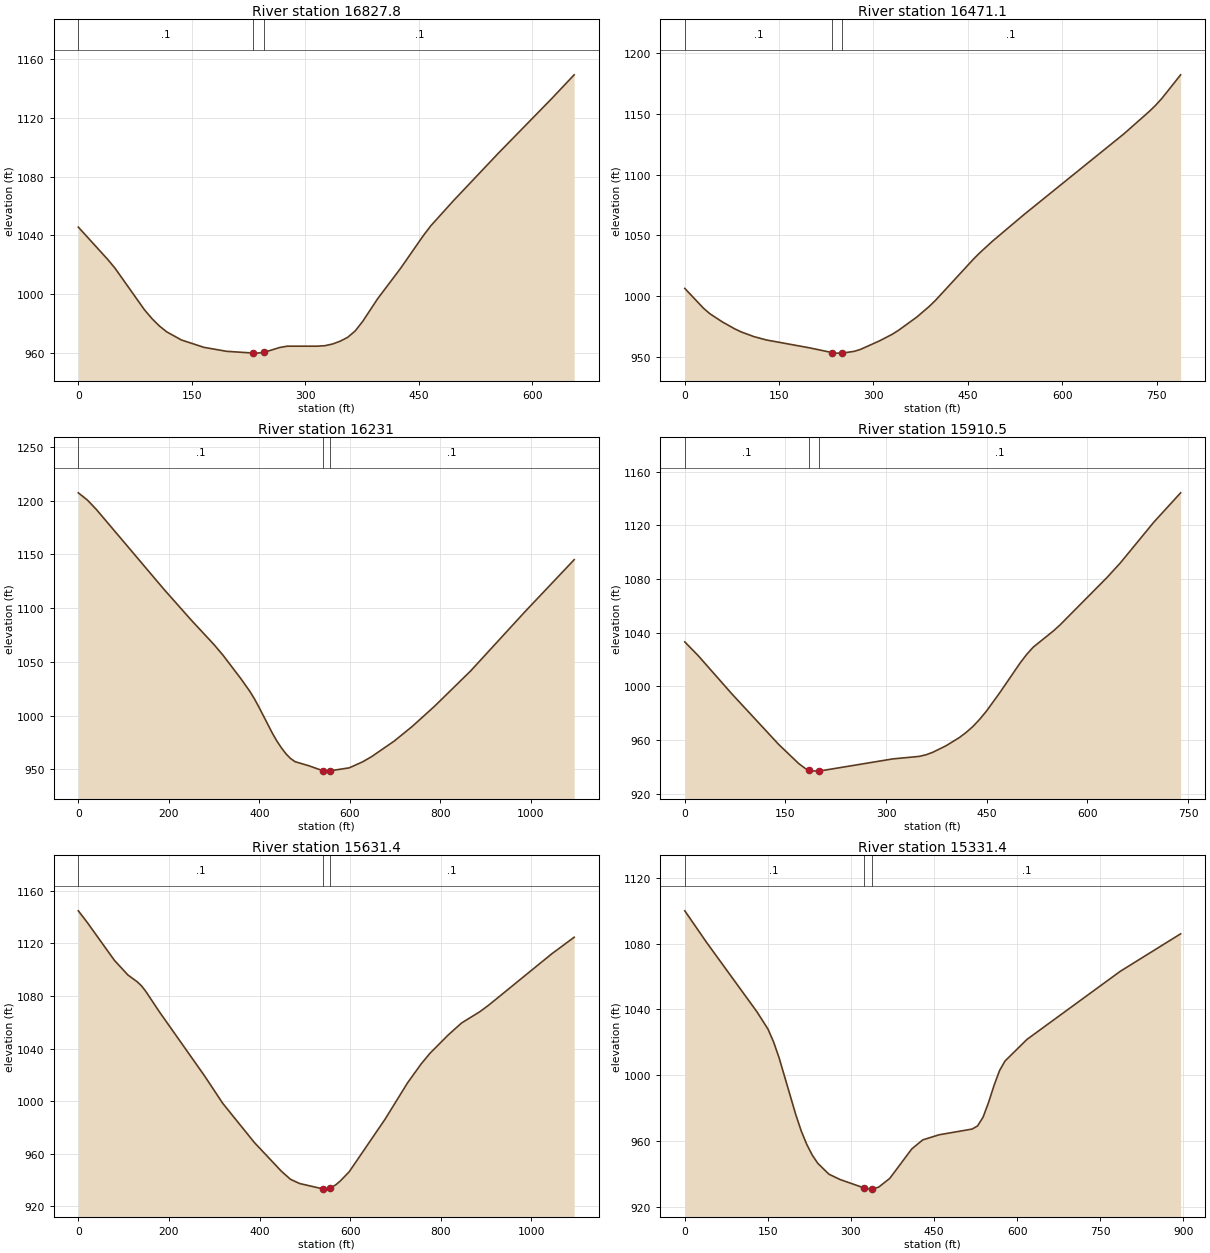
Type RM Length L Ch R = 1 ,16827.8 ,349.1,356.5,364
XS GIS Cut Line= 3
     1936628.199      438769.276     1936642.454      438904.705
     1936956.079       439318.12
#Sta/Elev= 30
       0 1045.69    38.9 1023.68    48.6 1017.66    87.5  989.38    97.3  983.47
     107   978.5   116.7  974.49   136.2  968.93   166.1   963.9     196  961.22
   230.9  960.04     236  959.99   245.9  960.59   265.9   963.8   275.9  964.71
   315.8  964.71   325.8  965.04   335.8  966.18   345.7  968.05   355.7  970.68
   365.7  975.01   375.7  981.57   395.6  997.08   425.6 1017.54   455.5 1039.68
   465.5 1046.46   495.4 1063.54   555.3 1096.14   625.2 1132.97   655.1 1149.27
#Mann= 3 , 0 , 0
       0      .1       0   230.9    .045       0   245.9      .1       0
Bank Sta=230.9,245.9
XS Rating Curve= 0 ,0
Exp/Cntr=0.3,0.1

Type RM Length L Ch R = 1 ,16471.1 ,236,240.1,241.8
XS GIS Cut Line= 2
     1936328.829      438920.743     1936567.312      439672.099
#Sta/Elev= 30
       0 1006.41    29.9  990.02    39.9  985.57    59.9  978.78    79.8  973.01
    89.8  970.58   109.8  966.76   129.7  963.98   199.6  957.37   234.6  953.56
   239.5  953.16   249.5  953.15   249.6  953.16   269.4  954.61   279.4  956.23
   309.3  963.18   329.3  968.53   339.3  971.74   369.2  982.97   389.2  991.85
   399.1  996.88     459 1030.55     469 1035.72   488.9 1045.16   538.8 1066.96
   698.5 1133.77   738.4 1152.03   748.4 1157.03   758.4 1162.72   788.3 1182.19
#Mann= 3 , 0 , 0
       0      .1       0   234.6    .045       0   249.6      .1       0
Bank Sta=234.6,249.6
XS Rating Curve= 0 ,0
Exp/Cntr=0.3,0.1

Type RM Length L Ch R = 1 ,16231   ,318.2,320.1,324.5
XS GIS Cut Line= 3
     1936102.149      438665.444     1936169.715      439210.239
     1936296.781      439741.989
#Sta/Elev= 30
       0 1207.23      20 1200.53    39.9 1191.75   189.6 1117.34   249.5 1088.92
   299.4 1066.32   319.4 1056.42   359.3 1034.37   379.3 1022.46   389.3 1015.56
   399.2 1007.91   429.2   983.4   439.2  976.14   449.2  969.85   459.1  964.45
   469.1  960.16   479.1  957.21     509  953.51   541.5  948.66     549  948.46
   556.5  948.78   598.7  951.51   628.5  957.16   648.4     962   698.1  976.42
   737.8  989.99   787.5 1008.92   867.1 1041.69   986.4 1096.42  1095.7 1145.04
#Mann= 3 , 0 , 0
       0      .1       0   541.5    .045       0   556.5      .1       0
Bank Sta=541.5,556.5
XS Rating Curve= 0 ,0
Exp/Cntr=0.3,0.1

Type RM Length L Ch R = 1 ,15910.5 ,282.8,278.9,274.5
XS GIS Cut Line= 2
     1935844.136      439018.751     1935872.305      439757.148
#Sta/Elev= 30
       0 1033.11      20 1022.86    69.9  994.54   139.8  956.83   169.8  942.49
   179.7  938.83     185  937.89   189.7  937.05   199.7  936.88     200   936.9
   309.6  945.95   349.5  947.87   359.5  949.07   369.5  950.89   389.4   955.8
   409.4  961.95   419.4  965.73   429.4  970.15   439.4  975.45   449.4  981.49
   469.3   995.2   499.3 1017.11   509.3 1023.68   519.2 1029.17   549.2 1041.24
   559.2 1045.76   629.1 1081.02   649.1 1091.94     699  1122.3   738.9 1144.12
#Mann= 3 , 0 , 0
       0      .1       0     185    .045       0     200      .1       0
Bank Sta=185,200
XS Rating Curve= 0 ,0
Exp/Cntr=0.3,0.1

Type RM Length L Ch R = 1 ,15631.4 ,306,300,293.4
XS GIS Cut Line= 3
      1935461.71      438696.764     1935575.036      439232.811
     1935703.689      439763.874
#Sta/Elev= 30
       0  1144.8    19.9 1135.87    79.7  1107.1   109.6 1095.92   129.5 1090.94
   139.5 1087.69   149.4 1083.24   179.3 1067.77   278.9 1019.04   318.8  998.28
   388.5   968.5   448.3   946.6   468.2   940.5   488.1  937.32   540.4  933.15
   547.9  933.02   555.4  933.76   567.8  936.21   577.7  939.08   597.6  946.13
     677  986.23   726.7 1013.95   756.5 1028.24   776.4 1036.51   816.1 1050.25
   845.9 1059.47   885.7 1067.93   905.6 1072.99  1044.6 1112.01  1094.3 1124.69
#Mann= 3 , 0 , 0
       0      .1       0   540.4    .045       0   555.4      .1       0
Bank Sta=540.4,555.4
XS Rating Curve= 0 ,0
Exp/Cntr=0.3,0.1

Type RM Length L Ch R = 1 ,15331.4 ,288.9,300,312.6
XS GIS Cut Line= 3
     1935138.479      439018.751     1935288.376      439313.226
     1935571.345      439801.981
#Sta/Elev= 30
       0 1099.88      40 1080.36   130.2  1038.5   150.2 1027.94   160.2 1020.24
   170.2 1010.56   200.3  975.99   210.3  965.91   220.3  957.74   230.3  951.19
   240.3  946.24   260.3  939.67   280.4  936.44   322.9  931.41   337.9   930.6
   350.2  931.85   370.1  937.15   409.7  955.01   429.5  960.54   459.2  963.66
   518.7  967.13   528.6  969.05   538.5  974.37   548.4  983.28   558.3  993.63
   568.2 1002.66   578.1 1008.51   617.8 1021.67   786.2 1063.08   895.2 1085.89
#Mann= 3 , 0 , 0
       0      .1       0   322.9    .045       0   337.9      .1       0
Bank Sta=322.9,337.9
XS Rating Curve= 0 ,0
Exp/Cntr=0.3,0.1

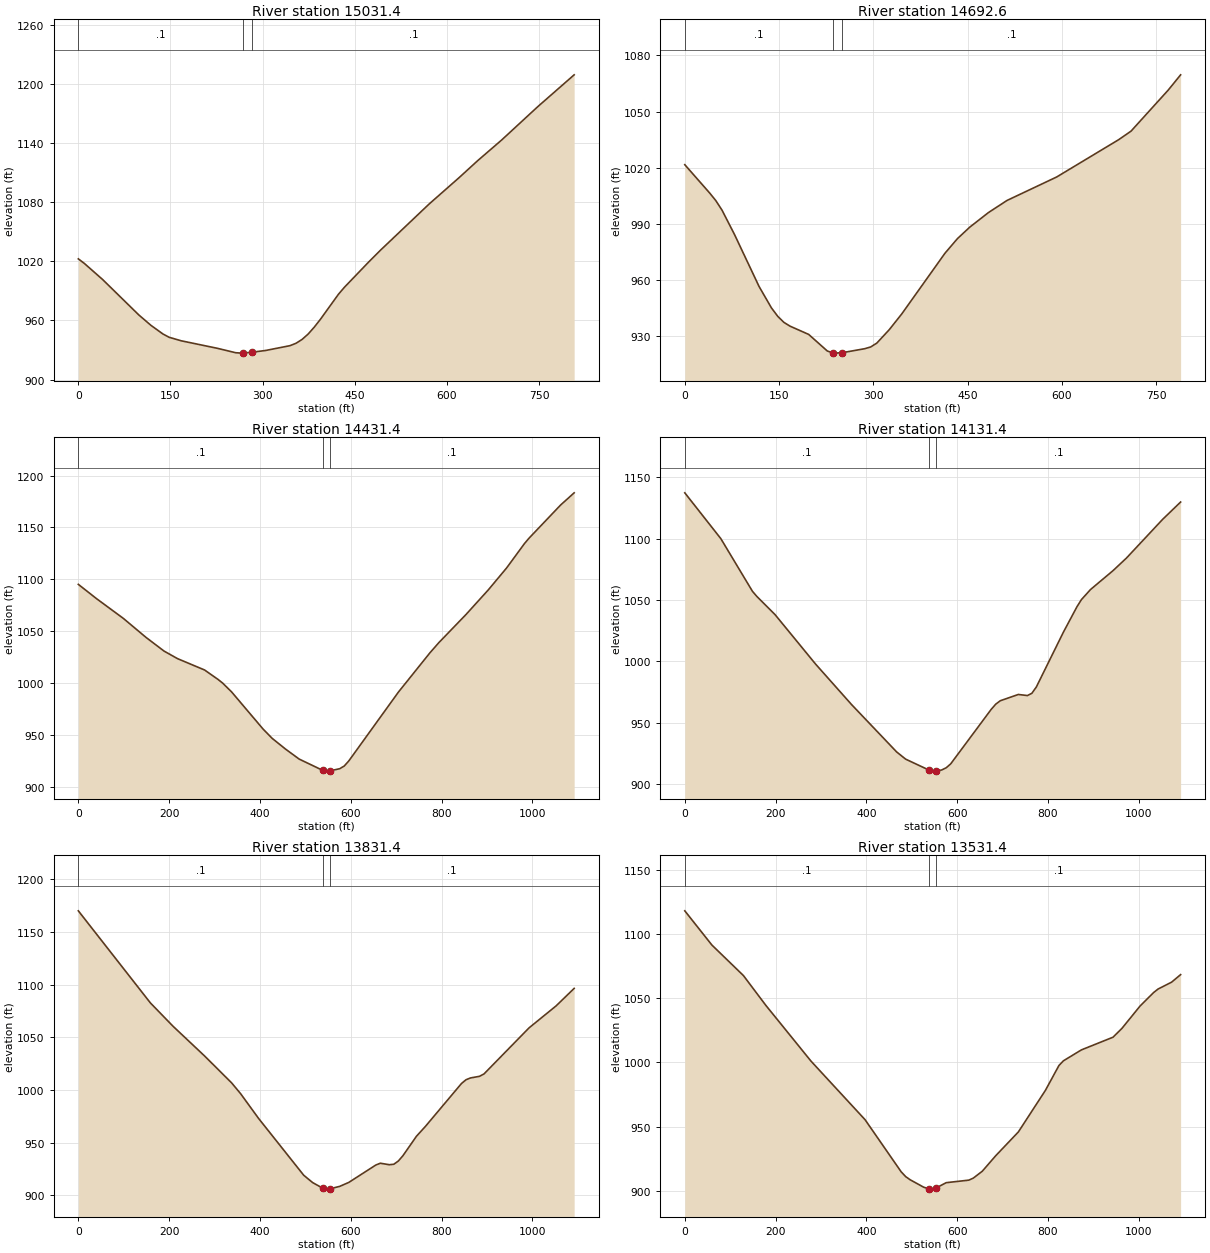
Type RM Length L Ch R = 1 ,15031.4 ,335.6,338.4,342.6
XS GIS Cut Line= 3
     1935058.291      439211.202     1935053.023      439486.947
      1935035.64      440017.952
#Sta/Elev= 30
       0 1022.53     9.8 1017.87    39.4 1001.62    98.5  965.55   118.2  955.01
   137.9  946.16   147.8  942.89   167.4  939.32   226.6  931.65   256.1  927.19
     266  926.79   268.3  926.88   283.3  927.74   305.3  929.53   344.7  934.39
   354.5  936.85   364.3  940.74   374.2  946.22     384  953.15   393.9  960.99
   423.4  986.55   433.2  993.72   472.6  1019.3   492.2 1031.52     571 1078.21
   620.2 1105.21   649.7 1122.04     689 1143.18     748 1177.16   807.1 1209.42
#Mann= 3 , 0 , 0
       0      .1       0   268.3    .045       0   283.3      .1       0
Bank Sta=268.3,283.3
XS Rating Curve= 0 ,0
Exp/Cntr=0.3,0.1

Type RM Length L Ch R = 1 ,14692.6 ,261.1,261.2,259.7
XS GIS Cut Line= 3
     1934771.395      439134.578     1934737.538      439378.707
      1934616.22      439907.752
#Sta/Elev= 30
       0 1021.59    39.4 1006.53    49.3 1002.43    59.2  997.32    78.9  984.43
   118.3  956.44     138     945   147.9  940.57   157.7  937.32   167.6  935.27
   197.2  930.87   226.8  922.02   235.4  921.01   236.6  920.87   250.4  921.09
   285.9   923.2   295.8  924.15   305.7  926.25   325.4  933.39   345.2  941.76
   414.2   974.3     434  982.08   453.7  988.24   483.3     996   512.9 1002.48
   591.9 1015.02   690.6 1034.96   710.3 1039.54   769.5 1061.48   789.2 1069.63
#Mann= 3 , 0 , 0
       0      .1       0   235.4    .045       0   250.4      .1       0
Bank Sta=235.4,250.4
XS Rating Curve= 0 ,0
Exp/Cntr=0.3,0.1

Type RM Length L Ch R = 1 ,14431.4 ,299.5,300,300.5
XS GIS Cut Line= 3
      1934562.07      438774.996     1934484.855      439315.508
      1934407.64      439856.021
#Sta/Elev= 30
       0 1095.06    39.7  1081.4    99.3 1062.18   148.9 1043.97   188.6 1030.77
   218.4 1023.44     278 1012.49   307.8 1003.34   317.7   999.9   337.5  991.37
     407  955.46   426.9  946.56   456.6  936.12   486.4  926.56   538.5  915.65
     546  914.95   553.5  915.14   575.8   917.3   585.7   919.9   595.6  924.73
   704.8  991.07   774.3 1029.01   794.2 1038.94   853.8 1065.98   903.4 1089.96
   943.1 1110.79   982.8 1134.51   992.7 1139.62  1062.2 1171.57    1092 1183.32
#Mann= 3 , 0 , 0
       0      .1       0   538.5    .045       0   553.5      .1       0
Bank Sta=538.5,553.5
XS Rating Curve= 0 ,0
Exp/Cntr=0.3,0.1

Type RM Length L Ch R = 1 ,14131.4 ,304.7,300,295.3
XS GIS Cut Line= 3
     1934279.687      438723.185     1934189.924      439261.756
     1934100.162      439800.327
#Sta/Elev= 30
       0 1137.34    79.4 1099.98   148.9 1057.15   158.8 1052.85   198.6 1038.16
   287.9  997.84   367.3  964.78   466.6  926.18   486.4  920.31   538.5  911.27
     546  910.54   553.5  910.57   565.8  911.48   575.8  913.28   585.7   916.5
     675  960.96     685  965.18   694.9  967.91   734.6  973.01   754.5  972.13
   764.4  973.98   774.3  979.15   833.9 1023.83   863.7 1044.51   873.6 1050.34
   893.4 1058.48   943.1 1073.91   972.9 1084.26  1052.3 1115.69    1092 1129.84
#Mann= 3 , 0 , 0
       0      .1       0   538.5    .045       0   553.5      .1       0
Bank Sta=538.5,553.5
XS Rating Curve= 0 ,0
Exp/Cntr=0.3,0.1

Type RM Length L Ch R = 1 ,13831.4 ,298.5,300,301.6
XS GIS Cut Line= 3
     1933869.405      438684.467     1933892.784      439229.966
     1933916.163      439775.465
#Sta/Elev= 30
       0 1169.96   158.8  1082.5   208.5 1060.43     278  1032.2   337.5 1006.69
   357.4  996.38   397.1  972.83   496.4  918.95   516.2  911.93   538.5  906.63
     546  905.77   553.5  905.99   575.8  908.41   595.6  912.13   655.2  928.65
   665.1  930.35     685  928.94   694.9  929.41   704.8  932.46   714.8  937.44
   744.6  955.91   764.4   965.3   843.8 1006.01   853.8 1009.59   863.7 1011.32
   883.5 1012.85   893.4  1015.1   992.7 1058.87  1052.3 1079.74    1092 1096.33
#Mann= 3 , 0 , 0
       0      .1       0   538.5    .045       0   553.5      .1       0
Bank Sta=538.5,553.5
XS Rating Curve= 0 ,0
Exp/Cntr=0.3,0.1

Type RM Length L Ch R = 1 ,13531.4 ,304,300,295.3
XS GIS Cut Line= 3
      1933606.59       438694.59     1933593.065      439240.426
     1933577.903      439786.215
#Sta/Elev= 30
       0 1118.14    59.6  1091.5   129.1 1067.68   178.7 1044.35     278 1000.95
   397.1  955.27   476.5   914.7   486.4  910.95   496.4  908.46   526.2  902.67
   538.5  901.29     546  901.18   553.5   902.1   575.8  906.21   625.4  908.18
   635.4  909.76   655.2  915.14     685   927.3   734.6  945.74   794.2  978.16
     824  997.55   833.9 1001.22   873.6 1009.75   943.1 1019.61     963  1026.6
  1002.7 1043.92  1032.4  1054.4  1042.4 1057.18  1072.2 1062.54    1092 1068.41
#Mann= 3 , 0 , 0
       0      .1       0   538.5    .045       0   553.5      .1       0
Bank Sta=538.5,553.5
XS Rating Curve= 0 ,0
Exp/Cntr=0.3,0.1

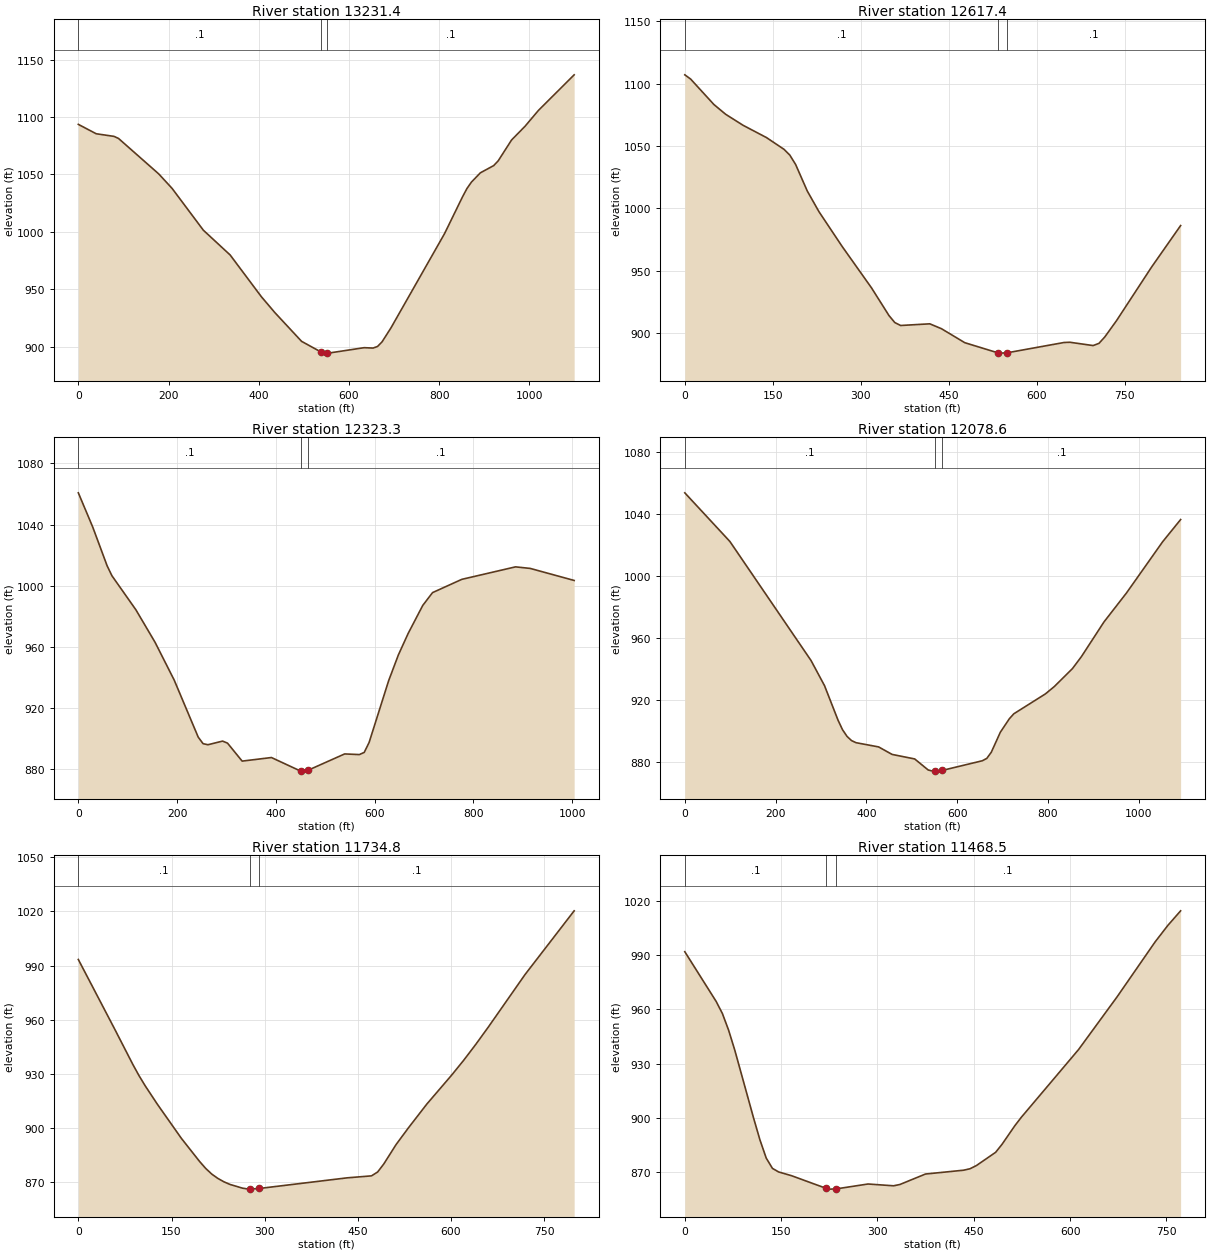
Type RM Length L Ch R = 1 ,13231.4 ,618.8,613.9,609.5
XS GIS Cut Line= 3
     1933209.805      438703.076     1933293.264      439241.079
     1933394.107      439786.574
#Sta/Elev= 30
       0 1093.54    39.6 1085.37    79.2 1083.08    89.1 1081.28   178.2 1050.42
   207.9 1037.77   277.2 1001.36   336.6   979.8   405.8  943.46   435.6  929.67
   494.9  904.62   536.9  895.55   551.9   894.4   554.3  894.35   633.6  899.09
   653.4  898.75   663.3  900.16   673.2   904.1     693  916.28   811.9  998.42
   851.5 1030.27   861.4 1037.58   871.3 1043.19   891.2 1051.33   920.9 1057.66
   930.8 1061.78   960.5 1079.96   990.2 1091.84  1019.9 1105.64  1099.2 1136.68
#Mann= 3 , 0 , 0
       0      .1       0   536.9    .045       0   551.9      .1       0
Bank Sta=536.9,551.9
XS Rating Curve= 0 ,0
Exp/Cntr=0.3,0.1

Type RM Length L Ch R = 1 ,12617.4 ,294.2,294.1,294.1
XS GIS Cut Line= 2
     1932522.263       438939.75     1932831.137      439726.189
#Sta/Elev= 30
       0 1107.02     9.9 1103.64    49.7 1083.17    69.6 1075.38    99.4 1066.52
   139.2 1056.69     169 1047.29   178.9 1042.68   188.9 1035.07   208.7 1013.84
   228.6  997.26   268.4  969.18   318.1  936.19   347.9  913.97   357.8  908.34
   367.8  905.96   417.5  907.31   437.4  903.37   477.1  892.17   533.2  884.07
   536.8   883.8   548.2  883.97   646.1  892.32   656.1  892.52   695.8  889.86
   705.8  891.65   715.7  896.78   735.6   909.8   795.2  952.68   844.9  986.11
#Mann= 3 , 0 , 0
       0      .1       0   533.2    .045       0   548.2      .1       0
Bank Sta=533.2,548.2
XS Rating Curve= 0 ,0
Exp/Cntr=0.3,0.1

Type RM Length L Ch R = 1 ,12323.3 ,247.4,244.7,242
XS GIS Cut Line= 3
      1932325.06      439129.826     1932374.955      439367.421
     1932655.787      440075.118
#Sta/Elev= 30
       0 1060.77    29.1 1038.39    58.3 1012.95      68 1006.44   116.5  984.14
   155.4  962.81   194.2     938   242.8  900.64   252.7  896.32   262.6  895.66
   292.2  898.03   302.1  896.71   331.8  884.91   391.1  887.26   450.4  878.35
   450.7  878.35   465.7  878.99   539.4  889.62   569.1  889.19     579  890.62
   588.9  897.12   628.4  937.55   648.2  954.52     668  968.59   697.6  986.97
   717.4  995.36   776.7 1004.06   885.5 1012.24   915.2 1011.22  1004.2 1003.33
#Mann= 3 , 0 , 0
       0      .1       0   450.7    .045       0   465.7      .1       0
Bank Sta=450.7,465.7
XS Rating Curve= 0 ,0
Exp/Cntr=0.3,0.1

Type RM Length L Ch R = 1 ,12078.6 ,352.5,343.7,334.8
XS GIS Cut Line= 3
     1931961.992      439169.279     1932222.305      439649.231
     1932482.618      440129.182
#Sta/Elev= 30
       0 1053.69    99.3 1022.26     278  945.35   307.8  929.05   337.5  906.78
   347.4  900.61   357.4  896.28   367.3  893.58   377.2  892.23   426.9   889.5
   456.6  884.65   506.3  881.73   536.1  874.59     546  873.86   551.8  873.87
   566.8  874.31   655.2  880.55   665.1  882.08     675  886.05   694.9  898.96
   714.8  907.71   724.7  910.92   794.2  923.76     814  928.56   853.8  940.12
   873.6  947.88   923.2  970.26   972.9  989.03  1052.3 1022.04    1092 1036.42
#Mann= 3 , 0 , 0
       0      .1       0   551.8    .045       0   566.8      .1       0
Bank Sta=551.8,566.8
XS Rating Curve= 0 ,0
Exp/Cntr=0.3,0.1

Type RM Length L Ch R = 1 ,11734.8 ,266.2,266.4,266.5
XS GIS Cut Line= 3
     1931707.313      439688.174      1931873.63       439790.34
     1932341.691      440170.491
#Sta/Elev= 30
       0  993.34    58.6  954.74    87.8  935.19    97.6  929.05   107.4   923.5
   126.9  913.34   165.9  894.26   195.2  881.47   205.1  877.59     215  874.41
   224.8  872.04   234.7  870.14   244.6  868.69   264.4  866.67   274.3  866.14
   276.5  866.16   291.5  866.51   432.4  872.38     472  873.49   481.9  875.65
   491.7  880.05   511.5  890.81   531.3  900.03   560.9   913.2   600.5  929.09
   620.2  937.44     640   946.4   659.8   955.8   719.1  984.99   798.2  1020.3
#Mann= 3 , 0 , 0
       0      .1       0   276.5    .045       0   291.5      .1       0
Bank Sta=276.5,291.5
XS Rating Curve= 0 ,0
Exp/Cntr=0.3,0.1

Type RM Length L Ch R = 1 ,11468.5 ,341.1,350.3,359.5
XS GIS Cut Line= 3
     1931617.027      439897.257     1931716.817      440004.175
     1932200.113      440401.637
#Sta/Elev= 30
       0  991.82    48.8  964.38    58.5  957.72    68.2  948.51      78  937.26
   107.2  899.85     117   887.9   126.8  877.84   136.5  872.16   146.2  870.18
   166.1  868.14   219.8  861.18   225.7  860.71   234.8  860.79   285.3  863.54
     325  862.55     335  863.28   374.7  869.04   434.3  871.17   444.2  871.98
   454.2  873.76     484  881.05   493.9  885.44   513.8  895.69   523.7  900.27
   613.1  937.79   672.7  966.71   732.3  997.25   752.1 1006.34     772  1014.4
#Mann= 3 , 0 , 0
       0      .1       0   219.8    .045       0   234.8      .1       0
Bank Sta=219.8,234.8
XS Rating Curve= 0 ,0
Exp/Cntr=0.3,0.1

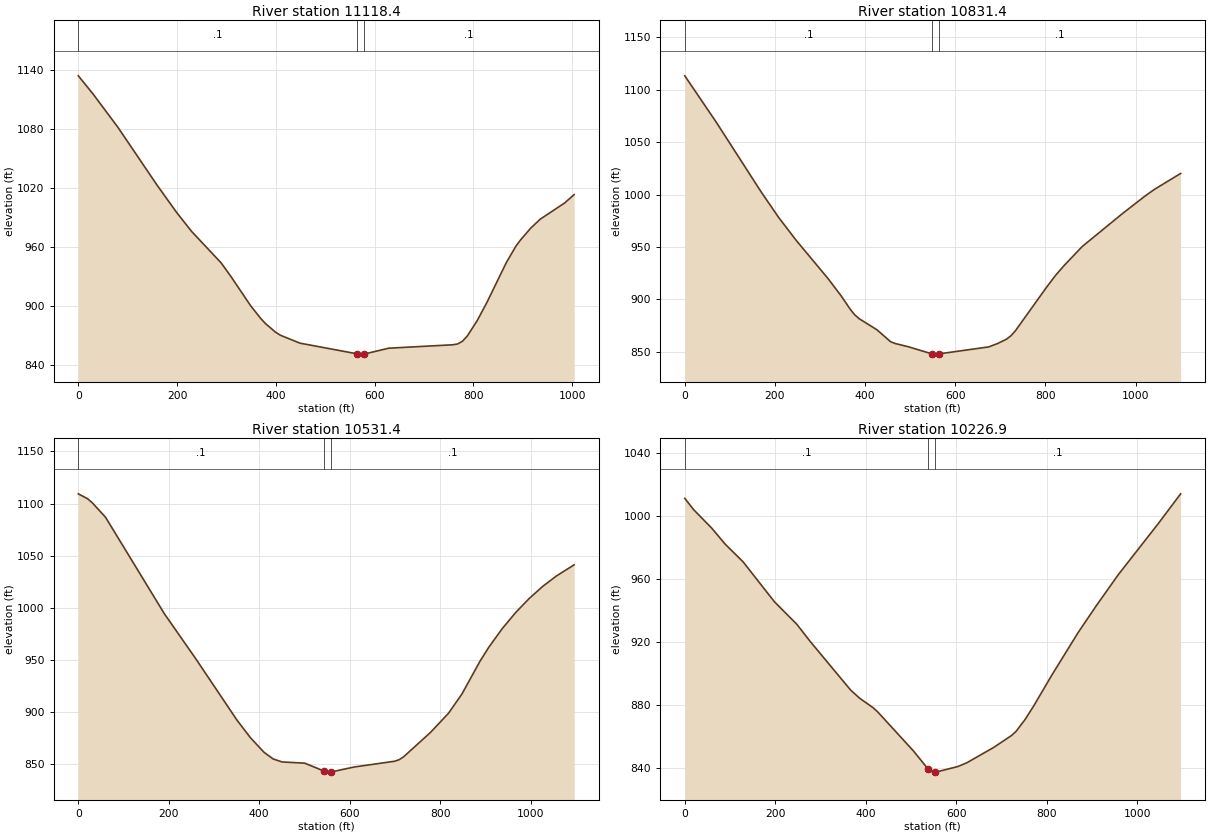
Type RM Length L Ch R = 1 ,11118.4 ,279.3,286.7,297.3
XS GIS Cut Line= 3
     1931260.442      439789.967     1931628.907      440486.492
     1931735.825      440674.192
#Sta/Elev= 30
       0 1133.99    29.9 1115.44    79.8 1081.86   159.6 1022.62   199.5  994.66
   229.4  975.61   289.3  943.54   309.2  929.61   349.1  899.88     369  887.23
     379  881.82     399   873.2     409     870   448.8  861.91   563.3  851.18
   578.3  850.75   628.4  856.78   758.1  860.26     768  861.09     778  863.94
     788  869.44   807.6  884.79   827.3  903.34   866.5  943.76   886.2  960.75
     896   967.3   915.6  978.72   935.3   988.1   984.4 1004.48    1004 1013.11
#Mann= 3 , 0 , 0
       0      .1       0   563.3    .045       0   578.3      .1       0
Bank Sta=563.3,578.3
XS Rating Curve= 0 ,0
Exp/Cntr=0.3,0.1

Type RM Length L Ch R = 1 ,10831.4 ,303.3,299.9,291.4
XS GIS Cut Line= 3
     1931179.785       439815.41     1931262.126      440364.591
     1931264.967        440909.2
#Sta/Elev= 30
       0 1113.11    69.4 1069.17   168.6 1002.98   208.2  978.14   247.9  955.87
   317.3  920.11   347.1  903.25   366.9  890.69   376.8  885.38   386.7  881.66
   426.4  871.02   456.2  859.79   466.1  858.04   495.8   854.9   547.8  848.16
   555.3  847.86   562.8  848.03   674.1  854.74     694  857.99   713.8  862.15
   723.7  865.44   733.6  870.24   802.9  911.85   822.7  923.06   842.5  932.79
   882.1  950.61   971.2  981.93  1020.7  998.44  1040.5 1004.53  1099.9 1020.07
#Mann= 3 , 0 , 0
       0      .1       0   547.8    .045       0   562.8      .1       0
Bank Sta=547.8,562.8
XS Rating Curve= 0 ,0
Exp/Cntr=0.3,0.1

Type RM Length L Ch R = 1 ,10531.4 ,305,304.2,305.9
XS GIS Cut Line= 3
     1930809.092      439895.556     1930972.821      440421.409
     1931177.901      440927.154
#Sta/Elev= 30
       0 1109.28      20 1104.69      30  1101.1    60.1 1086.88   190.3  994.33
   260.4  950.77   350.5  892.62   380.5  875.57   410.6  861.58   430.6  855.24
   450.6  852.29   500.7  851.14   543.3  843.57   550.8  842.54   558.3  842.62
   610.3  847.47   699.6  852.99   709.5  854.45   719.4  857.25     779  880.69
   818.7     899   848.4   917.5   888.1  948.71     908   962.4   937.7  980.23
   967.5  995.69   997.3 1009.06    1027 1020.58  1056.8 1030.41  1096.5 1041.26
#Mann= 3 , 0 , 0
       0      .1       0   543.3    .045       0   558.3      .1       0
Bank Sta=543.3,558.3
XS Rating Curve= 0 ,0
Exp/Cntr=0.3,0.1

Type RM Length L Ch R = 1 ,10226.9 ,296.8,300,302.3
XS GIS Cut Line= 3
     1930495.973      439961.584     1930680.136      440474.605
     1930851.203      440998.629
#Sta/Elev= 30
       0 1011.08    19.8 1003.85    59.5  992.21    89.2  982.06   128.8  970.86
   198.2  945.48   247.8  931.17   277.5  920.23   366.7  889.46   386.5  884.31
   416.2  878.29   426.2  875.71   505.4  850.88   537.6  839.48   545.1  837.81
   552.6  837.49   554.9  837.39   604.1  840.97   623.8  843.36   682.9  853.05
   722.3   860.6   732.1  863.14   751.8  870.54   771.5  879.39   810.8   898.6
   869.9  926.04   909.3  942.74   958.5  962.68  1047.1  995.16  1096.3 1013.97
#Mann= 3 , 0 , 0
       0      .1       0   537.6    .045       0   552.6      .1       0
Bank Sta=537.6,552.6
XS Rating Curve= 0 ,0
Exp/Cntr=0.3,0.1