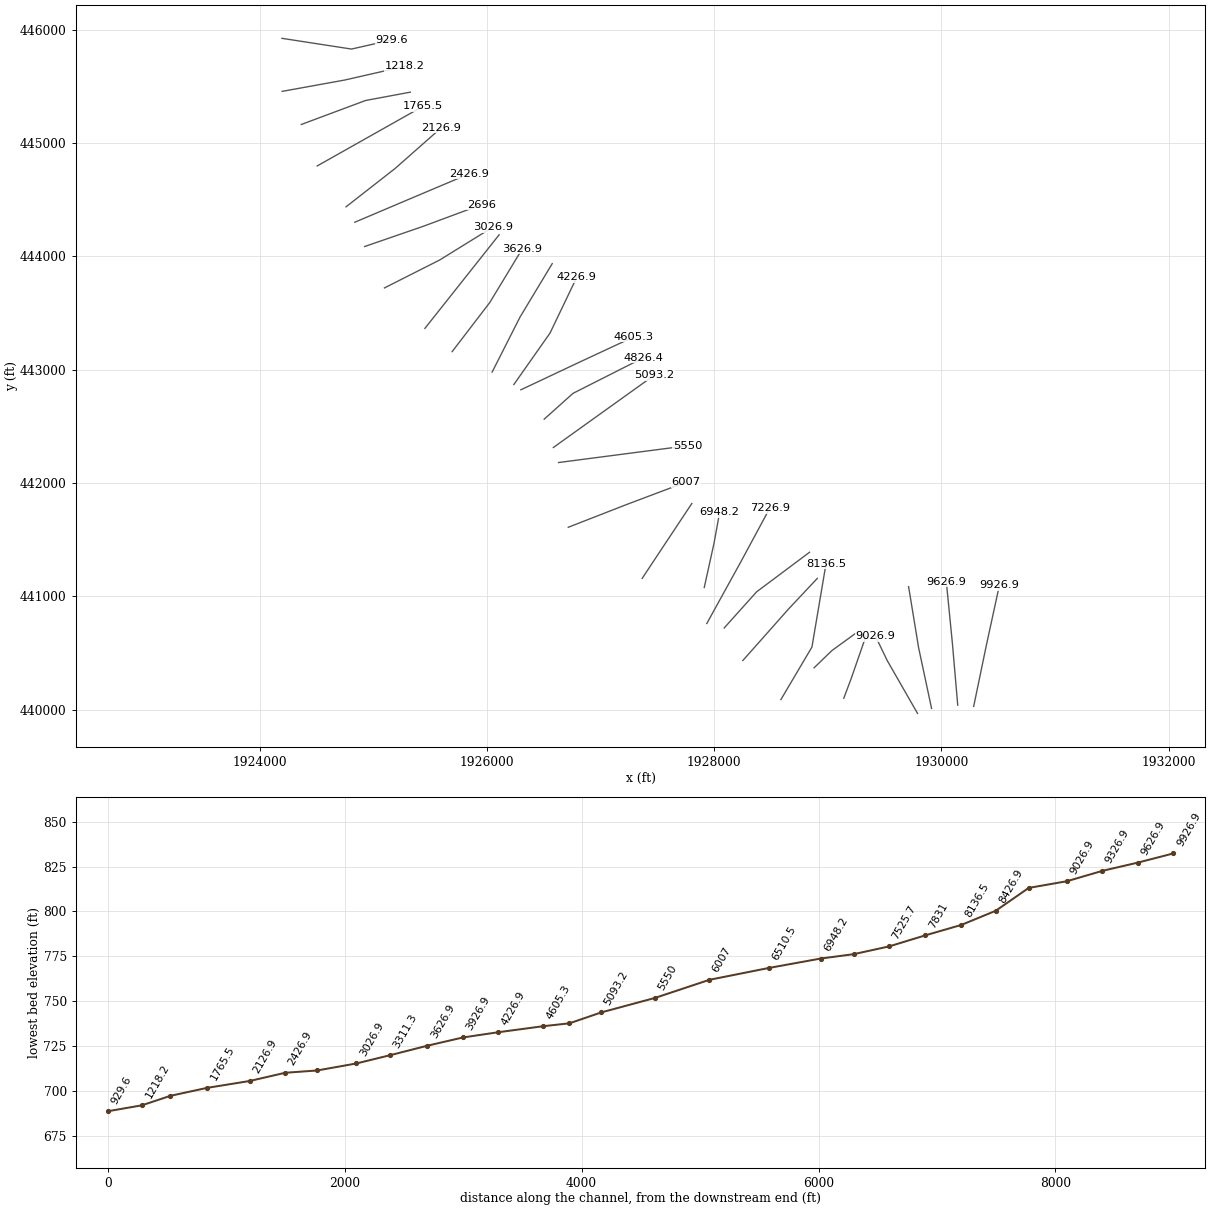
HEC-RAS study RichCreek.prj: RichCreek

--- RichCreek.g01 (geometry) --- (continued)

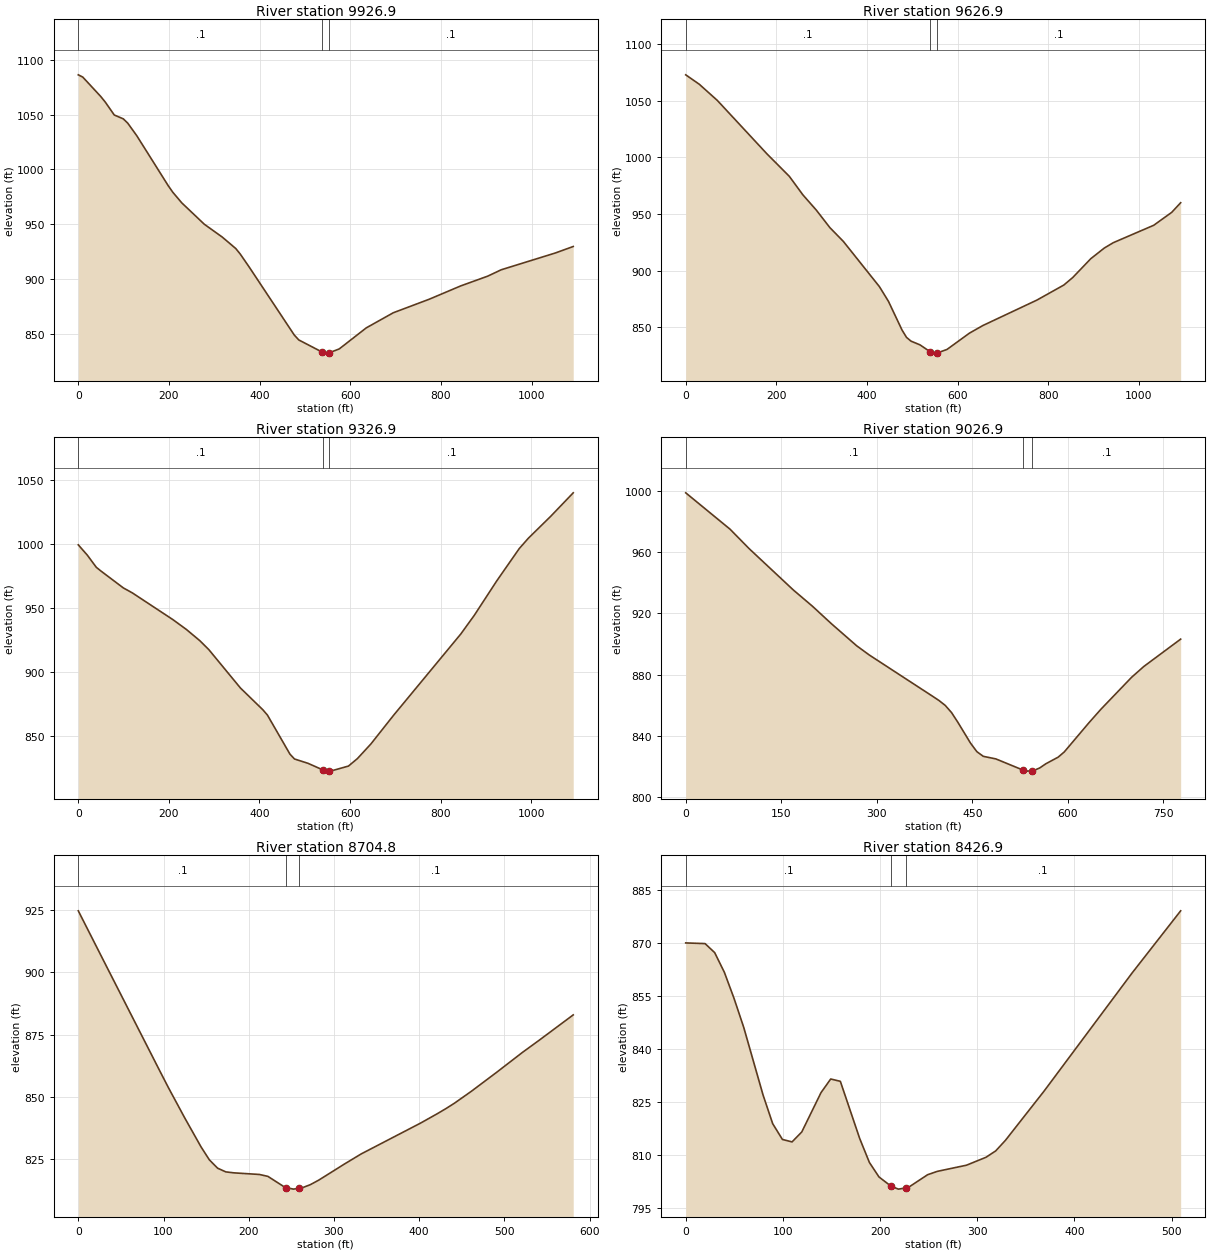
Type RM Length L Ch R = 1 ,9926.9  ,293.4,300,307
XS GIS Cut Line= 3
     1930284.699      440029.632     1930395.342      440564.334
     1930510.956      441097.948
#Sta/Elev= 30
       0 1086.45     9.9 1084.39    49.6 1066.65    59.6 1061.53    79.4 1049.76
    99.3 1046.26   109.2 1042.27   129.1 1030.82   198.6  985.11   208.5  979.25
   228.3  969.54     278  950.04   317.7  938.27   347.5  927.81   357.4  922.75
   377.3  910.79   476.5  848.87   486.5  844.36   538.5  833.18     546  832.32
   553.5  832.61   575.8  836.17   635.4  855.38   694.9  869.16   774.4  881.55
   843.8   893.7   903.4  902.62   933.2  908.44  1052.3  923.73    1092  929.69
#Mann= 3 , 0 , 0
       0      .1       0   538.5    .045       0   553.5      .1       0
Bank Sta=538.5,553.5
XS Rating Curve= 0 ,0
Exp/Cntr=0.3,0.1

Type RM Length L Ch R = 1 ,9626.9  ,297.2,300,301.4
XS GIS Cut Line= 3
     1930144.253      440040.885     1930097.346      440585.805
      1930043.87       441128.75
#Sta/Elev= 30
       0 1072.98    29.8  1064.7    69.6 1050.44     179  1003.3   228.7  983.33
   258.6  966.99   288.4  953.44   318.2  938.04     348  925.84   427.6  885.89
   447.5  872.95   477.3  847.74   487.3  841.14   497.2  837.82   517.1  834.51
   539.4  828.47   546.9  827.21   554.4  827.24   576.7  830.46   626.3  844.86
     656   851.6   775.1  874.03   834.6  887.34   854.4  894.02   894.1   910.6
   923.9     920   943.7  924.73    1033  940.11  1072.7  951.51  1092.5  960.03
#Mann= 3 , 0 , 0
       0      .1       0   539.4    .045       0   554.4      .1       0
Bank Sta=539.4,554.4
XS Rating Curve= 0 ,0
Exp/Cntr=0.3,0.1

Type RM Length L Ch R = 1 ,9326.9  ,293,300,306.5
XS GIS Cut Line= 3
     1929913.885      440012.048     1929799.972      440546.804
     1929711.821      441085.506
#Sta/Elev= 30
       0  999.34    19.9  991.31    39.8  981.79    49.7  978.97    99.4  965.71
   119.3  961.82   208.8  940.95   238.6  933.26   268.4  924.46   288.3  917.45
   357.9  887.55   407.6  870.47   417.5   866.4   467.2  835.92   477.2   832.1
     507  828.72   539.3  823.67   554.3  822.65   556.7  822.61   596.4  826.56
   616.2   832.4     646  843.85   695.6  866.04   844.5  929.75   874.3  944.36
   923.9  971.25   973.5  996.44   993.4 1004.44    1043 1021.66  1092.6 1039.96
#Mann= 3 , 0 , 0
       0      .1       0   539.3    .045       0   554.3      .1       0
Bank Sta=539.3,554.3
XS Rating Curve= 0 ,0
Exp/Cntr=0.3,0.1

Type RM Length L Ch R = 1 ,9026.9  ,341.4,322.1,304.4
XS GIS Cut Line= 3
     1929790.233      439968.006     1929523.696      440433.867
     1929419.275      440650.433
#Sta/Elev= 30
       0  998.98    69.6  975.18    99.4  962.52     169  935.38   198.8  924.83
   228.6  913.37   268.4  898.88   288.2  892.85   387.6  865.85   397.6  863.08
   407.5  859.85   417.4  855.16   427.4  848.75   447.3  835.11   457.2  829.56
   467.2  826.52     487  824.83   529.2  817.59   536.7  816.83   544.2   817.1
   546.3  817.18     556  818.95   565.6  821.67   584.8  825.96   594.4  829.38
   632.9  848.36   652.1  857.39   700.2  878.26   719.4  885.34   777.2  903.23
#Mann= 3 , 0 , 0
       0      .1       0   529.2    .045       0   544.2      .1       0
Bank Sta=529.2,544.2
XS Rating Curve= 0 ,0
Exp/Cntr=0.3,0.1

Type RM Length L Ch R = 1 ,8704.8  ,288.3,277.9,264.1
XS GIS Cut Line= 3
     1929141.289      440101.589      1929205.44      440272.657
     1929335.874      440648.773
#Sta/Elev= 30
       0  924.63    28.8  905.26    96.2  860.11   105.8  853.75     125   841.6
   144.2  829.95   153.8  824.85   163.5   821.5   173.1  820.02   182.7  819.63
   212.6  818.98   222.5  818.22   242.4  813.86   244.1  813.73   252.4  813.11
   259.1  813.43   262.3  813.58   272.3   814.9   282.2  816.72   312.1  823.12
     332  827.22   401.6  839.56   421.6  843.39   431.5  845.39   441.5  847.56
   461.4  852.35   491.2  859.99   521.1  867.87     541  872.81   580.8  882.93
#Mann= 3 , 0 , 0
       0      .1       0   244.1    .045       0   259.1      .1       0
Bank Sta=244.1,259.1
XS Rating Curve= 0 ,0
Exp/Cntr=0.3,0.1

Type RM Length L Ch R = 1 ,8426.9  ,276.1,290.3,307.8
XS GIS Cut Line= 3
     1928879.935      440370.071      1929037.12      440522.308
     1929271.966        440693.2
#Sta/Elev= 30
       0  869.97    19.9  869.78    29.8  867.23    39.8  861.65    49.7  854.31
    59.7   846.1    79.6  826.98    89.5  818.89    99.5  814.44   109.4  813.74
   119.4  816.55   139.2  827.66   149.2  831.52   159.1  830.87     179  814.72
     189  807.94   198.9  803.83   211.3  801.23   218.8   800.4   226.3  800.72
   228.8  800.83   248.9  804.47   258.9  805.42   288.9  807.16     309   809.4
     319  811.21     329  814.19     369  828.19   459.2  861.43   509.3  879.04
#Mann= 3 , 0 , 0
       0      .1       0   211.3    .045       0   226.3      .1       0
Bank Sta=211.3,226.3
XS Rating Curve= 0 ,0
Exp/Cntr=0.3,0.1

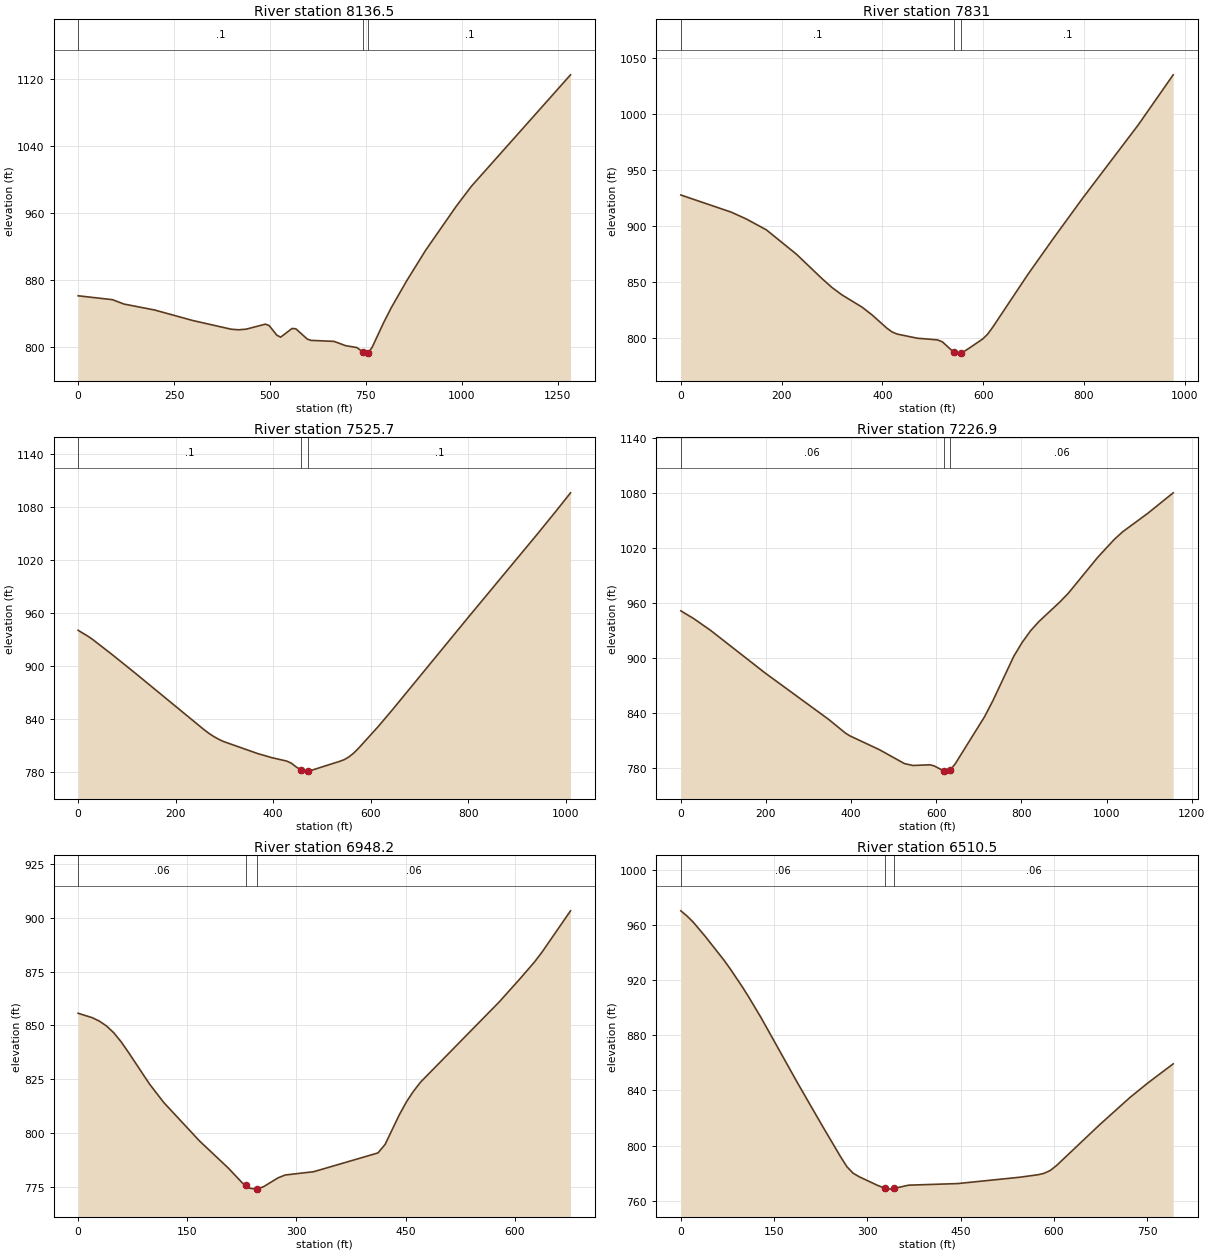
Type RM Length L Ch R = 1 ,8136.5  ,318,305.4,292.7
XS GIS Cut Line= 3
     1928587.693      440089.709     1928860.927      440553.019
     1928985.023      441288.505
#Sta/Elev= 30
       0  861.12    89.6  856.46   119.5  851.23   199.2  844.13   298.8  831.55
   398.4  821.18   418.4  820.42   438.3  821.21   488.1  827.18     498   825.5
     518  813.99   527.9  811.62   557.8  822.02   567.7  821.61   597.6  809.24
   607.5  807.77   667.2  806.58     697   801.5   726.8  799.18   741.7  794.11
   746.7  792.52   756.7  793.12   766.6  799.57   796.4   828.9   816.3  846.78
   856.1  878.65   905.8  915.44   985.4  967.99  1025.2  992.11  1283.8 1125.49
#Mann= 3 , 0 , 0
       0      .1       0   741.7    .045       0   756.7      .1       0
Bank Sta=741.7,756.7
XS Rating Curve= 0 ,0
Exp/Cntr=0.3,0.1

Type RM Length L Ch R = 1 ,7831    ,309.8,305.2,300.7
XS GIS Cut Line= 3
     1928252.685      440434.222     1928656.596      440890.404
     1928908.446      441158.886
#Sta/Elev= 30
       0   927.8    99.9  912.52   129.8  906.44   169.8   896.7   229.7  874.89
   279.7  853.42   299.7   845.4   319.6  838.73   359.6  827.78   379.6  820.79
   409.5  808.79   419.5  805.57   429.5  803.69   469.5  799.99   509.4  798.53
   519.4   796.7   539.4  788.47   541.8  788.04   549.4  786.69   556.8  787.22
   559.4  787.41   569.4  790.22   599.3  799.32   609.3  803.71   619.2  809.84
   688.9  856.88   738.6  888.46   798.3  925.33   907.8   990.2   977.4 1035.03
#Mann= 3 , 0 , 0
       0      .1       0   541.8    .045       0   556.8      .1       0
Bank Sta=541.8,556.8
XS Rating Curve= 0 ,0
Exp/Cntr=0.3,0.1

Type RM Length L Ch R = 1 ,7525.7  ,289.2,298.9,308.8
XS GIS Cut Line= 3
     1928088.744      440721.711     1928373.858      441040.088
     1928839.781       441389.14
#Sta/Elev= 30
       0  939.97    19.9  933.33    29.8  929.56    69.6  912.54   119.3  890.47
   258.4  827.35   268.4   823.2   278.3  819.64   288.2  816.61   298.2  814.04
   367.8  800.48   397.6  795.72   427.4  791.96   437.2  789.51   447.1  785.27
   457.3  781.79   466.8  780.54   472.3   780.9   476.7  781.19   535.9  791.56
   545.8  793.57   555.6  796.79   565.5  801.22   575.4  806.72   614.9   830.8
   644.5  850.08   802.3  956.26   940.5  1048.2     980 1075.02  1009.6 1095.61
#Mann= 3 , 0 , 0
       0      .1       0   457.3    .045       0   472.3      .1       0
Bank Sta=457.3,472.3
XS Rating Curve= 0 ,0
Exp/Cntr=0.3,0.1

Type RM Length L Ch R = 1 ,7226.9  ,272,278.5,284.9
XS GIS Cut Line= 3
      1927935.46      440760.646     1928236.629      441307.673
      1928488.71      441776.181
#Sta/Elev= 30
       0     951    29.7  942.73    69.4  929.89   198.2  883.17   346.9  832.77
   386.6  817.72   396.5  814.82   465.9  799.74   525.3  784.45   545.2  782.37
   584.8  783.13   594.7  782.01     617   776.6   624.4  776.23     632  777.87
   634.3  778.37   644.2  783.97   713.1   835.3   732.8  852.85   782.1   901.5
   801.8  916.61   821.5   929.3   841.2   939.4   890.5  960.75   910.2  970.22
   979.1 1009.31  1018.5 1029.07  1038.2 1037.36  1097.4 1057.57  1156.5  1079.7
#Mann= 3 , 0 , 0
       0     .06       0     617    .045       0     632     .06       0
Bank Sta=617,632
XS Rating Curve= 0 ,0
Exp/Cntr=0.3,0.1

Type RM Length L Ch R = 1 ,6948.2  ,446,437.7,429.4
XS GIS Cut Line= 3
     1927912.924      441078.104     1927999.382      441470.934
     1928048.353      441740.993
#Sta/Elev= 30
       0  855.67    19.6   853.6    29.4  851.97    39.2   849.7      49  846.58
    58.9  842.47    68.7  837.72    98.1  822.72   117.7  814.11   166.8  796.22
     206  783.72   225.6   776.7   230.3  775.52   235.4  774.24   245.3  773.79
   255.1  774.98   274.7  779.04   284.5  780.36   323.8  781.91     412  790.64
   421.8  794.58   441.4  808.41   451.2  814.44     461  819.44   470.8  823.69
   578.7  860.96   608.1  872.07   627.7  879.78   637.5  884.15   676.7  903.38
#Mann= 3 , 0 , 0
       0     .06       0   230.3    .045       0   245.3     .06       0
Bank Sta=230.3,245.3
XS Rating Curve= 0 ,0
Exp/Cntr=0.3,0.1

Type RM Length L Ch R = 1 ,6510.5  ,517.3,503.5,489.5
XS GIS Cut Line= 2
     1927366.456      441158.886     1927803.631      441819.399
#Sta/Elev= 30
       0  970.15     9.9  966.42    19.8  962.04    39.6  951.45    69.3  934.49
    79.2  928.29      99  915.03   108.9  907.96   128.7  893.06   188.1  845.23
   227.7  814.33   257.4  791.73   267.3  784.73   277.2  780.07   287.1  777.47
   316.8  771.22   328.7  769.12   336.6  768.55   343.7   769.1   366.3  771.41
   445.6  772.58   544.6  777.13   574.3  778.95   584.2  779.98   594.1     782
     604  785.46   673.3  815.01   722.8  835.05   752.5  845.86   792.1  859.28
#Mann= 3 , 0 , 0
       0     .06       0   328.7    .045       0   343.7     .06       0
Bank Sta=328.7,343.7
XS Rating Curve= 0 ,0
Exp/Cntr=0.3,0.1

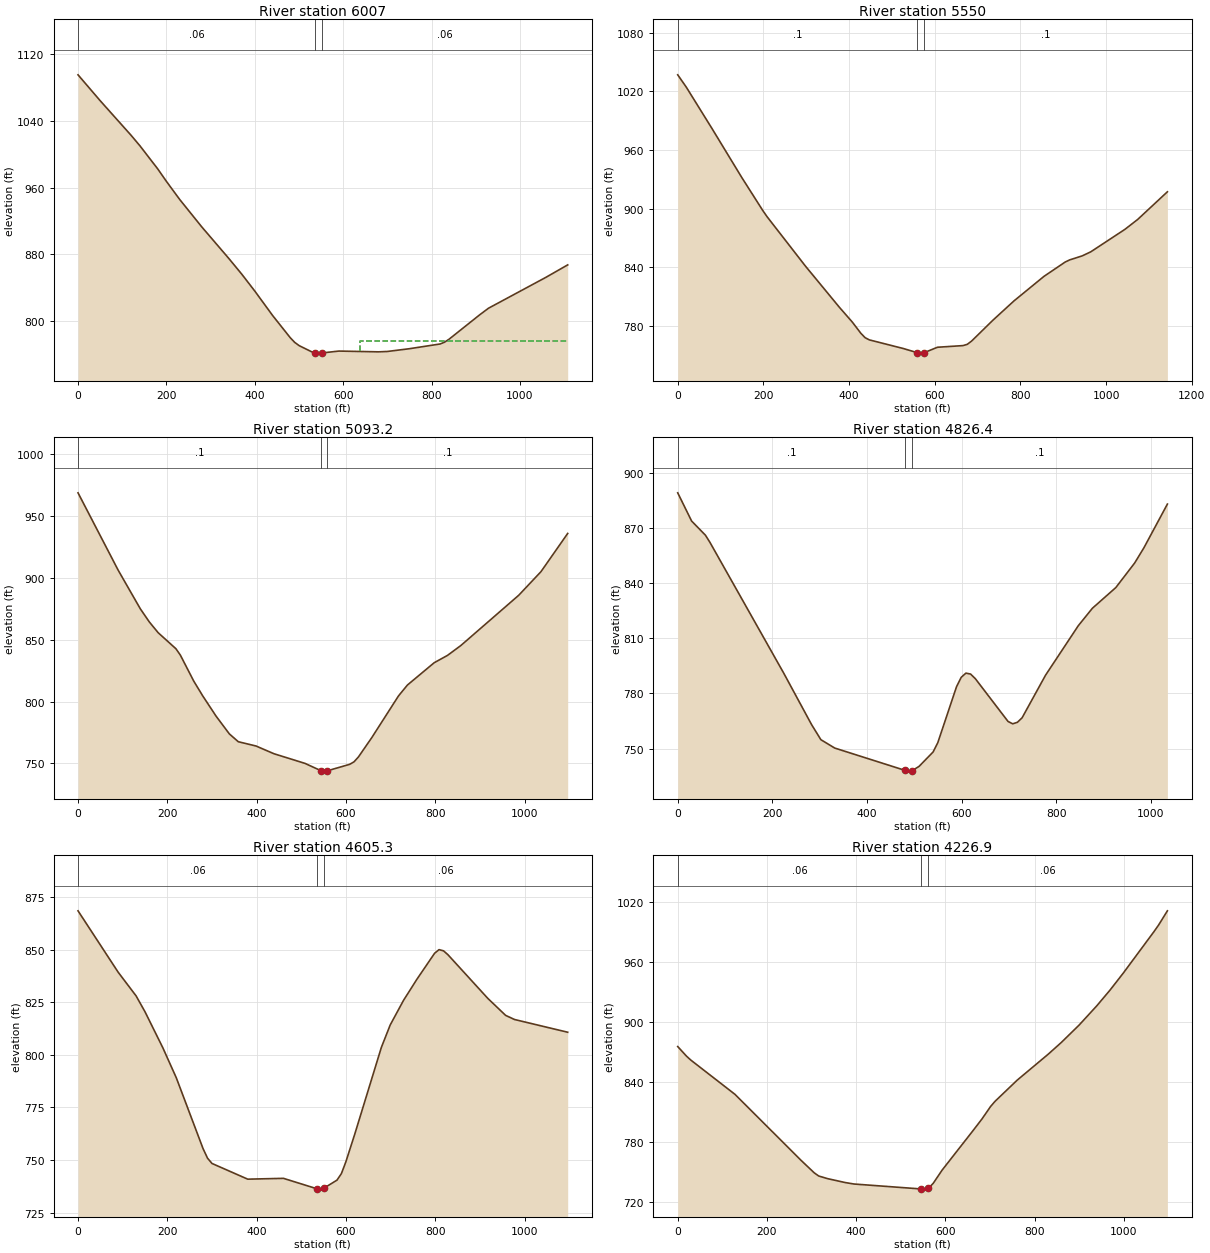
Type RM Length L Ch R = 1 ,6007    ,461.9,457,453
XS GIS Cut Line= 3
     1926715.827      441609.497     1927228.651      441809.896
     1927750.257      442006.885
#Sta/Elev= 30
       0 1094.99      50 1064.11   120.1 1022.61   140.2 1009.99   180.2  982.54
   200.2  967.36   230.2  945.75   280.3  912.84   340.4  875.77   370.4  856.54
   400.4  835.96   440.5  806.88   480.5  780.24   490.5  774.74   500.5  770.87
   530.6  763.04   536.1  762.42   540.6  761.92   551.1  762.09   590.4  764.38
     680  763.46   699.9  763.89   749.7  767.18   819.4  772.86   829.4  774.99
   839.3   778.4     909  807.76   928.9  815.64  1058.4  852.48  1108.2  867.53
#Mann= 3 , 0 , 0
       0     .06       0   536.1    .045       0   551.1     .06       0
#XS Ineff= 2 , 0
                          638.13           776.3
Permanent Ineff=
       F       F
Bank Sta=536.1,551.1
XS Rating Curve= 0 ,0
Exp/Cntr=0.3,0.1

Type RM Length L Ch R = 1 ,5550    ,445.8,456.5,466.5
XS GIS Cut Line= 2
     1926630.454      442180.558     1927764.032      442328.553
#Sta/Elev= 30
       0 1037.07    19.9 1024.52    79.5  982.41   149.1  932.18   198.8  897.89
   208.8  891.58   298.2  841.05   377.8  798.67   407.6   783.7   427.5  772.26
   437.4  767.75   447.3  765.47   526.9  756.59   559.1  752.37   566.6  751.89
   574.1  752.14   606.4  757.91     666   759.6     676  760.91   685.9  764.16
   735.6  785.52   785.3   805.5   854.9  830.49   904.6  845.24   914.6  847.35
   944.4  851.56   964.3  855.69  1043.8  878.65  1073.6  888.79  1143.2   917.2
#Mann= 3 , 0 , 0
       0      .1       0   559.1    .045       0   574.1      .1       0
Bank Sta=559.1,574.1
XS Rating Curve= 0 ,0
Exp/Cntr=0.3,0.1

Type RM Length L Ch R = 1 ,5093.2  ,270.3,266.8,263.3
XS GIS Cut Line= 2
     1926584.507      442313.085     1927475.071      442952.375
#Sta/Elev= 30
       0  968.85    89.7  906.41   139.5  875.03   159.5  864.48   179.4  855.72
   219.2  842.75   229.2  837.54   259.1  816.56     279  804.73     309  788.27
   338.8  773.87   358.8  767.55   398.6  764.07   438.5  757.85   508.3     750
   543.1  744.25   548.1  743.76   558.1  744.02   607.9  749.22   617.9  751.27
   627.9  755.28   657.8  770.92   717.6  804.64   737.5   813.4   797.3  831.41
   827.2  837.36   857.1  845.35   986.6  885.97  1036.5   905.1  1096.3  936.01
#Mann= 3 , 0 , 0
       0      .1       0   543.1    .045       0   558.1      .1       0
Bank Sta=543.1,558.1
XS Rating Curve= 0 ,0
Exp/Cntr=0.3,0.1

Type RM Length L Ch R = 1 ,4826.4  ,221.8,221.2,220.5
XS GIS Cut Line= 3
     1926503.987      442563.071     1926758.213      442791.162
     1927376.444      443104.509
#Sta/Elev= 30
       0  889.27    29.3  873.93    58.6  866.18    68.3   862.2   224.4  790.89
     283  762.99   302.5  754.85   331.8  750.29   480.4  738.13   490.1  737.73
   495.4     738   509.9   740.3   539.6  748.15   549.5  753.19   589.1  783.67
     599  788.79   608.9  791.09   618.8  790.59   628.7  788.13     698  764.77
   707.9  763.49   717.8  764.32   727.7  766.78   777.2  789.96   846.5  816.94
   876.2  826.41   925.7  837.68   965.4  851.01   985.2   859.4  1034.7  883.14
#Mann= 3 , 0 , 0
       0      .1       0   480.4    .045       0   495.4      .1       0
Bank Sta=480.4,495.4
XS Rating Curve= 0 ,0
Exp/Cntr=0.3,0.1

Type RM Length L Ch R = 1 ,4605.3  ,366.7,378.4,394
XS GIS Cut Line= 3
      1926298.87      442822.121     1926796.229      443057.268
     1927291.421      443288.657
#Sta/Elev= 30
       0  868.51      90  839.28     130  828.07     150   820.5     190  803.35
   220.1  789.09   280.1  755.36   290.1  750.84   300.1  748.33   380.1  740.87
   460.1  741.26   536.3  736.22   540.1  736.13   551.3  736.67     580  740.41
   589.9  743.53   599.8  749.08   619.7  762.22   679.3   803.5   699.2  814.22
     729  825.92   758.8   835.9   798.6  848.32   808.5  850.05   818.5  849.49
   828.4  847.65   917.8  826.86   957.6  818.79   977.5  816.82  1096.7  810.76
#Mann= 3 , 0 , 0
       0     .06       0   536.3    .045       0   551.3     .06       0
Bank Sta=536.3,551.3
XS Rating Curve= 0 ,0
Exp/Cntr=0.3,0.1

Type RM Length L Ch R = 1 ,4226.9  ,296.7,300,297.8
XS GIS Cut Line= 3
     1926237.108      442868.977     1926554.958      443321.748
     1926789.985      443813.167
#Sta/Elev= 30
       0  875.55    19.8  865.86    29.6  861.91   128.4  827.67   276.6  761.57
   306.2  749.05   316.1  745.92   335.9  743.29   375.4  739.38   395.1   737.9
   545.7  732.95   553.2  732.78   560.7  733.73   563.1  734.04     573  738.68
   592.8  751.82   662.2  791.43     682  802.94   701.8  815.72   711.7  820.81
   761.2  841.92   830.5  867.81   860.2  879.69   899.8  896.97   939.5  916.28
   969.2  932.01   998.9  949.04  1068.2  990.85  1078.1  997.16  1097.9 1011.44
#Mann= 3 , 0 , 0
       0     .06       0   545.7    .045       0   560.7     .06       0
Bank Sta=545.7,560.7
XS Rating Curve= 0 ,0
Exp/Cntr=0.3,0.1

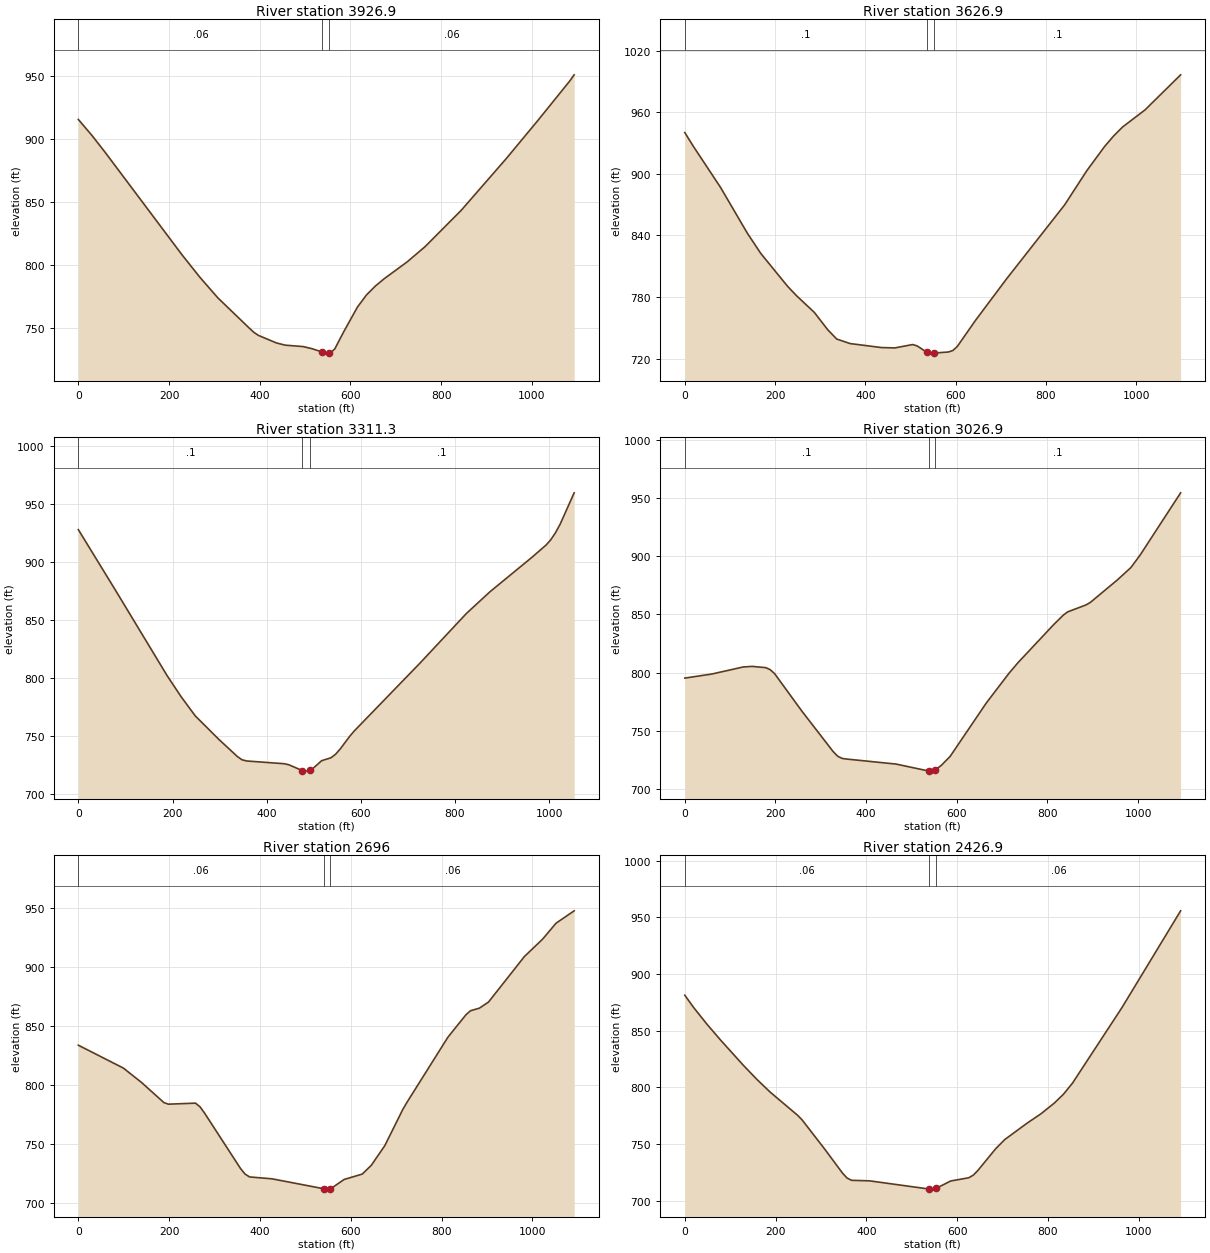
Type RM Length L Ch R = 1 ,3926.9  ,304.2,300,300
XS GIS Cut Line= 3
     1926045.888      442978.644     1926292.328      443465.514
     1926574.679      443934.906
#Sta/Elev= 30
       0  915.52    29.8  902.94    59.5  889.24   228.2  808.19   267.9   790.2
   307.6  773.81     377  749.72   386.9  746.45   396.9  743.98   436.6  737.98
   456.4  736.17   496.1  735.04   515.9  733.33   538.2  730.65   545.7  729.85
   553.2  729.87   555.6  729.87   565.6  733.22   585.5  746.96   615.4  766.34
   635.3     776   655.2  783.19   675.2  789.16     725  802.29   764.8  814.48
   844.5  843.35   944.1  884.57  1013.8  914.85  1083.5  945.95  1093.5  950.98
#Mann= 3 , 0 , 0
       0     .06       0   538.2    .045       0   553.2     .06       0
Bank Sta=538.2,553.2
XS Rating Curve= 0 ,0
Exp/Cntr=0.3,0.1

Type RM Length L Ch R = 1 ,3626.9  ,315.8,315.5,312.7
XS GIS Cut Line= 3
     1925693.768      443158.832     1926024.596      443591.432
     1926311.339      444065.738
#Sta/Elev= 30
       0  940.32    19.8  926.36    79.2  886.87   138.6  842.23   168.3  822.53
   227.7  790.47   247.6  781.26   287.2   764.9   316.9  748.01   336.7     739
   366.4  734.58   435.7   730.7   465.4  730.34     505  733.62   514.9   732.3
   537.1  725.93   544.6  725.26   552.1  725.32   584.2  726.37   594.1  727.83
     604  731.81   643.6  756.82   712.8  797.52   841.5  869.66     891  903.21
   930.6  926.91   950.4  937.03   970.2  945.78  1019.7  962.35  1098.8  996.64
#Mann= 3 , 0 , 0
       0      .1       0   537.1    .045       0   552.1      .1       0
Bank Sta=537.1,552.1
XS Rating Curve= 0 ,0
Exp/Cntr=0.3,0.1

Type RM Length L Ch R = 1 ,3311.3  ,294.2,284.4,276.6
XS GIS Cut Line= 2
     1925453.818      443363.766      1926107.35      444189.372
#Sta/Elev= 30
       0  928.16    79.5  875.51   188.7   802.2   218.5     784   248.3  767.61
     298  747.51   337.7  732.56   347.7  729.74   357.6  728.72   437.1  726.36
     447  725.47     476  720.38   486.8  719.97     491   720.7   496.7  721.68
   516.6  728.94   536.4  731.46   546.4  734.55   556.3  739.13   576.2  749.92
   586.1  754.63   725.2  812.92   824.5  856.01   874.2  874.59   963.6  904.37
   993.4   914.9  1003.3  919.38  1013.2  925.39  1023.2  932.81    1053  959.88
#Mann= 3 , 0 , 0
       0      .1       0     476    .045       0     491      .1       0
Bank Sta=476,491
XS Rating Curve= 0 ,0
Exp/Cntr=0.3,0.1

Type RM Length L Ch R = 1 ,3026.9  ,333.9,330.9,326.4
XS GIS Cut Line= 3
     1925097.855      443720.681     1925584.485      443967.329
     1926050.618      444256.328
#Sta/Elev= 30
       0  795.27    59.5  798.75     129  804.83   148.8  805.32   178.6  804.25
   188.5   802.5   198.4  798.98   257.9  767.13   327.3  732.17   337.3  728.17
   347.2  726.28   357.1  725.74   466.2  721.43   538.1  715.47   545.6  715.37
   553.1  716.57   565.5  720.15   585.4  727.99   665.2  773.86   715.1  799.32
     735  808.45   814.8  841.58   834.8  849.21   844.7  852.14   884.6     858
   894.6   860.2   954.4  879.57   984.3  890.22  1004.3  900.73    1094  954.39
#Mann= 3 , 0 , 0
       0      .1       0   538.1    .045       0   553.1      .1       0
Bank Sta=538.1,553.1
XS Rating Curve= 0 ,0
Exp/Cntr=0.3,0.1

Type RM Length L Ch R = 1 ,2696    ,267.6,269.1,270.1
XS GIS Cut Line= 3
     1924923.724      444085.948     1925439.731      444264.321
     1925951.567      444454.963
#Sta/Elev= 30
       0  833.81    99.3  814.34     139  802.19   188.6  785.01   198.5  783.68
   258.1  784.56     268  781.46     278  776.14   357.4  728.94   367.3  724.27
   377.2  721.85   426.8  720.23   540.4  711.82     546  711.48   555.4   711.7
   585.7  719.73   625.4  724.25   645.3   731.7   675.1  748.43   714.8  779.24
   724.7  785.73   814.1   840.6   853.8  859.65   863.8  863.08   883.6   865.3
   903.5  870.46   982.9  909.29  1022.6  923.88  1052.4  937.52  1092.2     948
#Mann= 3 , 0 , 0
       0     .06       0   540.4    .045       0   555.4     .06       0
Bank Sta=540.4,555.4
XS Rating Curve= 0 ,0
Exp/Cntr=0.3,0.1

Type RM Length L Ch R = 1 ,2426.9  ,294.1,300,307.3
XS GIS Cut Line= 3
     1924836.532      444300.064     1925339.028      444513.642
     1925841.875      444726.385
#Sta/Elev= 30
       0   881.3    19.8  870.29    49.6  855.34    79.4  841.46     129  819.45
   158.8  807.02   188.6   795.6   248.2  775.44   258.1  771.41   307.8   745.7
   347.5  724.26   357.4  719.96   367.3  717.98     407  717.51   538.5  710.25
     546   710.2   553.5  710.88   585.7   717.4   625.4  720.22   635.4  722.55
   645.3  726.58     685     746   704.8  753.97   754.5  768.59   784.3  776.65
     814  786.19   833.9  793.91   853.8   803.7     963   870.5    1092  955.76
#Mann= 3 , 0 , 0
       0     .06       0   538.5    .045       0   553.5     .06       0
Bank Sta=538.5,553.5
XS Rating Curve= 0 ,0
Exp/Cntr=0.3,0.1

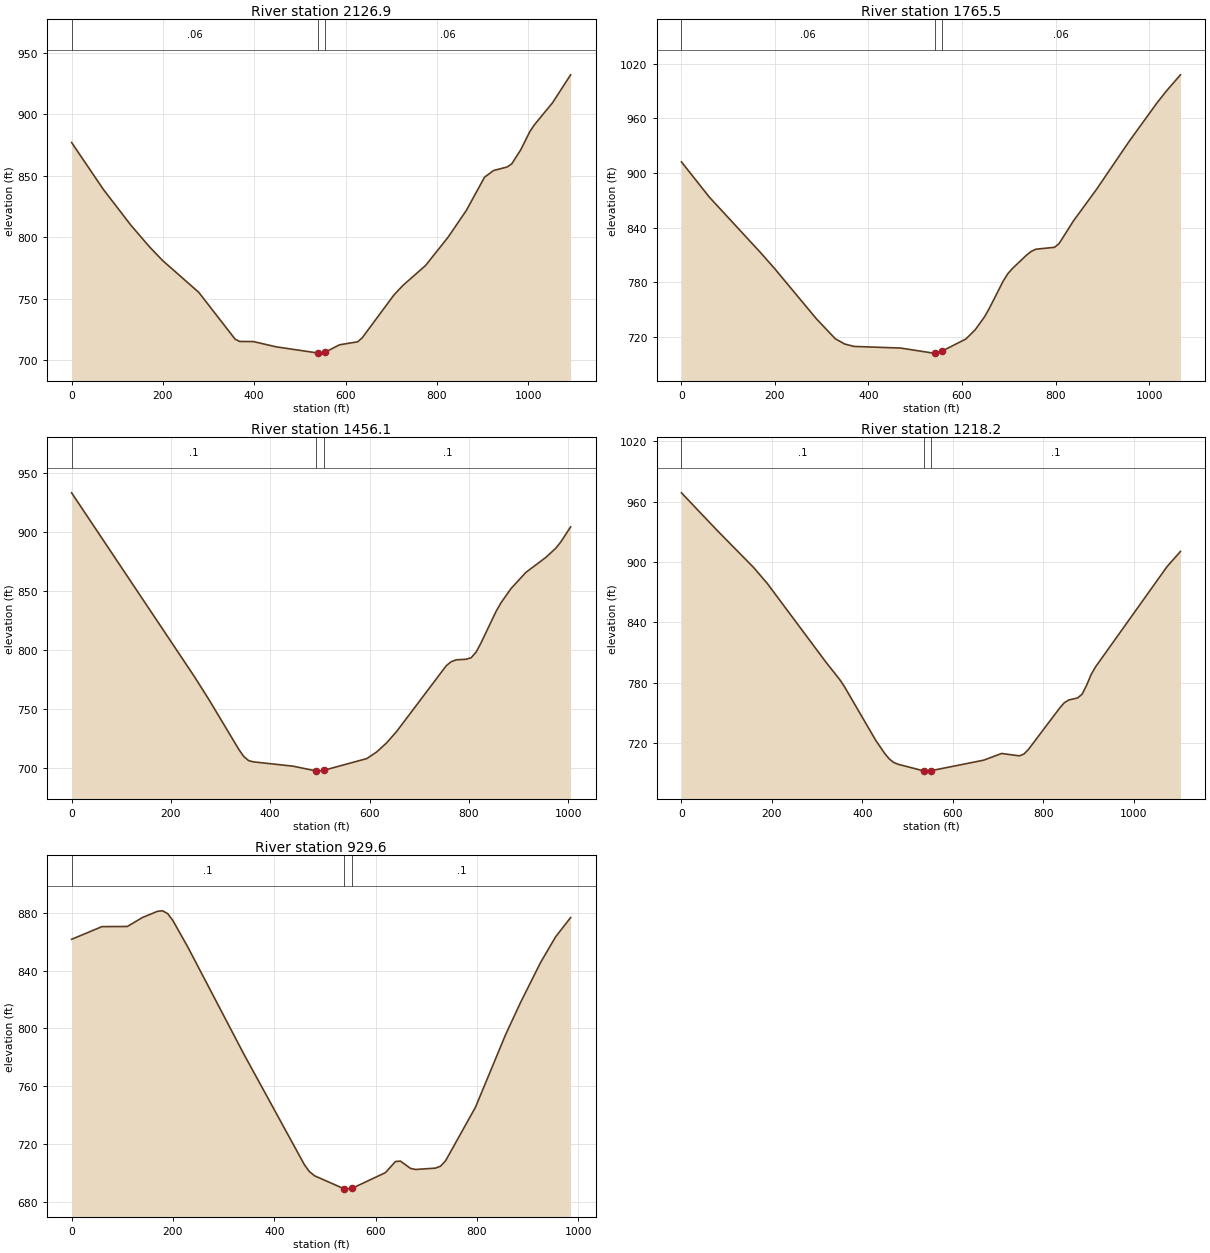
Type RM Length L Ch R = 1 ,2126.9  ,364.7,361.3,356.6
XS GIS Cut Line= 3
     1924759.709      444436.143     1925190.584      444773.415
     1925599.562      445134.838
#Sta/Elev= 30
       0  876.95    69.6  838.78   129.3  809.96   169.1   792.7     199  781.07
   278.6  755.05   358.2  716.96   368.1  715.11     398  715.04   447.7  710.77
   539.7   705.7   547.2  705.63   554.7  706.31   586.9  712.42   626.6  714.84
   636.5  718.08     706  752.94   725.8  760.75   775.4  776.96     825  800.12
   864.7  821.79   904.4  848.72   924.3  854.18     954  857.08     964  859.59
   983.8  871.07  1003.7  885.86  1013.6  891.37  1053.3  909.26    1093  932.03
#Mann= 3 , 0 , 0
       0     .06       0   539.7    .045       0   554.7     .06       0
Bank Sta=539.7,554.7
XS Rating Curve= 0 ,0
Exp/Cntr=0.3,0.1

Type RM Length L Ch R = 1 ,1765.5  ,312.8,309.2,305.6
XS GIS Cut Line= 2
     1924505.714      444796.579      1925434.81      445321.547
#Sta/Elev= 30
       0  912.22    59.8  873.36   169.6  812.15   199.5  794.67   289.2   739.2
   329.1  717.56   349.1  711.81     369  709.16   468.8  707.34   538.6  701.78
   541.4  701.91   556.4  703.75   608.4  717.37   628.3  727.54   648.3  741.84
   658.2  750.83   688.2   781.2   698.1  789.23   708.1  795.04     738  809.62
     748   813.7     758  816.12   797.9  818.21   807.8   822.4   837.8  846.88
   887.6  881.93   957.4  934.76  1017.3  977.34  1037.2  990.26  1067.2 1008.01
#Mann= 3 , 0 , 0
       0     .06       0   541.4    .045       0   556.4     .06       0
Bank Sta=541.4,556.4
XS Rating Curve= 0 ,0
Exp/Cntr=0.3,0.1

Type RM Length L Ch R = 1 ,1456.1  ,242.2,238.1,234.4
XS GIS Cut Line= 3
     1924365.634      445162.358     1924931.666      445373.933
     1925325.517      445447.472
#Sta/Elev= 30
       0  933.07   247.7  777.14   277.4  757.35   336.8  715.71   346.7  709.75
   356.6  706.22   366.5  705.18   445.8  701.55   493.1  697.45   495.3  697.35
   508.1  698.08   594.4  707.97   614.3  713.57   634.3  721.26   654.4  730.87
   754.5  786.66   764.5  790.06   774.6  791.62   794.6  792.11   804.6  793.39
   814.6  798.18   824.6  806.06   854.7   832.6   864.7  839.92   884.7  851.91
   914.8  865.69   954.9  878.33   974.9  886.08   984.9  891.33  1004.9  904.24
#Mann= 3 , 0 , 0
       0      .1       0   493.1    .045       0   508.1      .1       0
Bank Sta=493.1,508.1
XS Rating Curve= 0 ,0
Exp/Cntr=0.3,0.1

Type RM Length L Ch R = 1 ,1218.2  ,296.1,288.6,280.8
XS GIS Cut Line= 3
     1924197.646      445454.429     1924748.161       445554.39
     1925278.161      445675.453
#Sta/Elev= 30
       0   968.7    79.9   930.9   159.9  894.31   189.8  878.61   319.7  800.25
   349.7  783.21   359.7  776.56   429.6  722.66   449.6  709.52   459.6  704.16
   469.6  700.62   479.6  698.83   536.1  692.29   539.5  692.11   551.1  692.49
   668.2     703   707.8  709.65   747.3  707.29   757.2  709.13   767.1  713.64
   836.3  754.89   846.2  759.98     856  762.78   875.8  764.84   885.7  768.55
   895.6  777.37   905.5   787.9   915.4  795.68  1073.5  895.35  1103.2  910.45
#Mann= 3 , 0 , 0
       0      .1       0   536.1    .045       0   551.1      .1       0
Bank Sta=536.1,551.1
XS Rating Curve= 0 ,0
Exp/Cntr=0.3,0.1

Type RM Length L Ch R = 1 ,929.6   ,913.3,929.3,945.4
XS GIS Cut Line= 3
     1924195.484      445922.204      1924807.56      445827.624
     1925163.952      445908.406
#Sta/Elev= 30
       0   861.7    59.9  870.48   109.9  870.57   139.8  876.79   169.8  881.11
   179.8  881.41   189.8  879.41   199.8  874.72   229.8  856.05   339.6  782.44
   459.5  705.64   469.5  700.86   479.5  698.03   538.5  688.89   539.4  688.79
   553.5  689.35   619.3   700.2   639.1   707.9     649  708.17   668.7  703.16
   678.6  702.39   718.1  703.33     728  704.67   737.9  708.33   797.1  745.54
   856.4  795.66     886  817.98   925.5  845.63   955.1  863.38   984.8  876.77
#Mann= 3 , 0 , 0
       0      .1       0   538.5    .045       0   553.5      .1       0
Bank Sta=538.5,553.5
XS Rating Curve= 0 ,0
Exp/Cntr=0.3,0.1

Chan Stop Cuts=-1
Use User Specified Reach Order=0
Composite Channel Slope=5